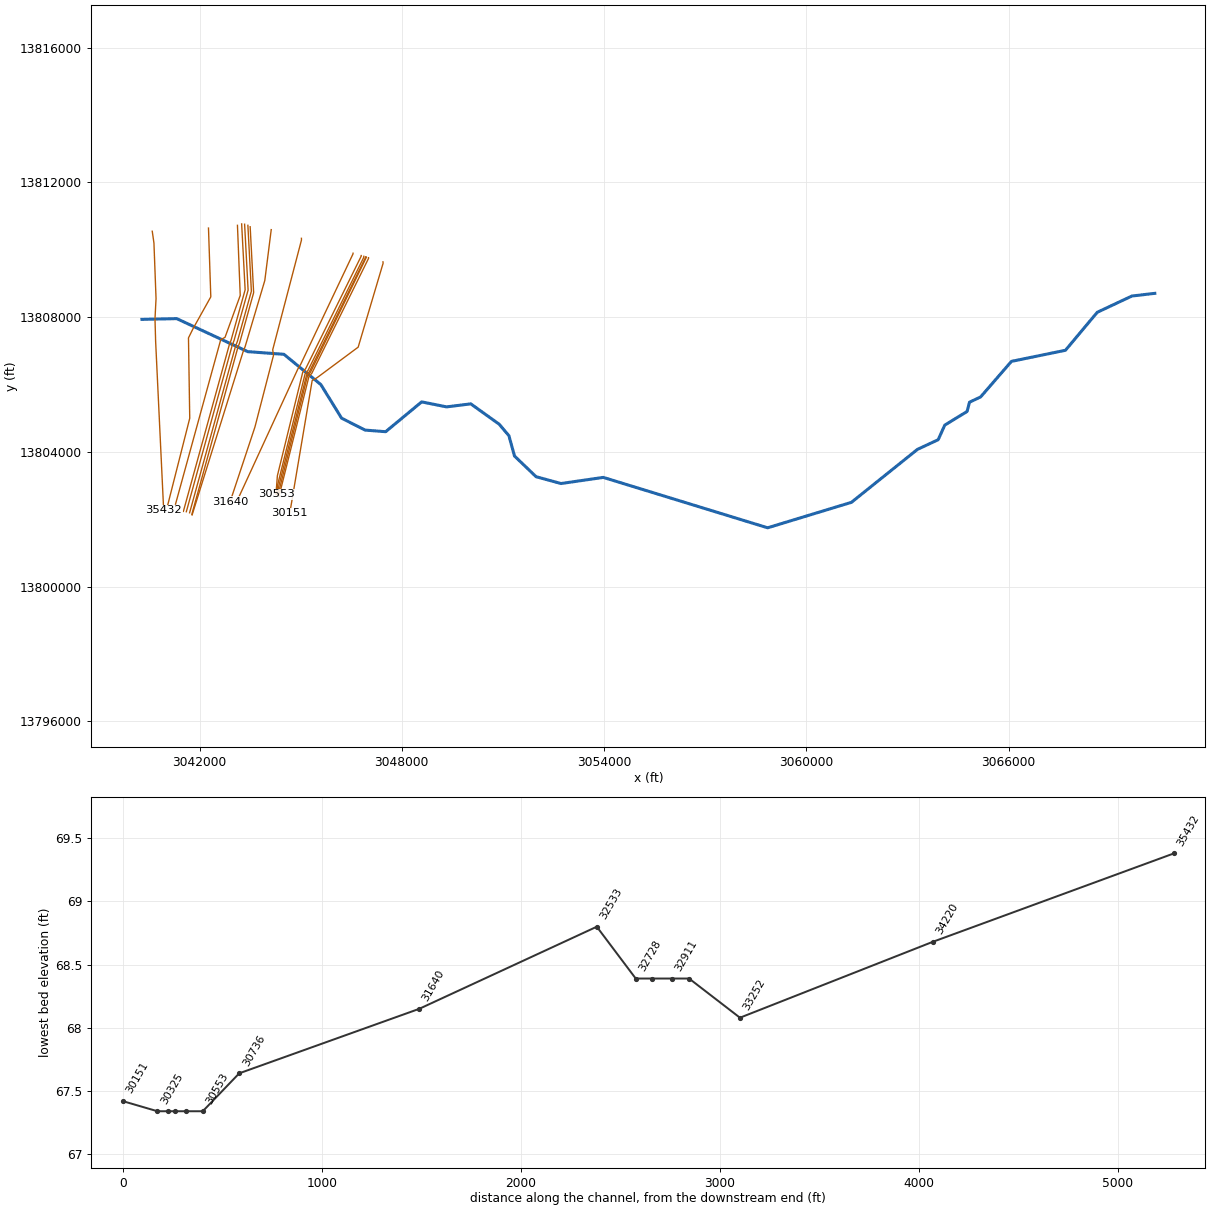
--- D118-00-00.prj (project) ---

Proj Title=D118-00-00
Current Plan=p06
Default Exp/Contr=.3,.1
English Units
Geom File=g03
Flow File=f04
Flow File=f05
Flow File=f02
Plan File=p05
Plan File=p06
Plan File=p01
Y Axis Title=Elevation
X Axis Title(PF)=Main Channel Distance
X Axis Title(XS)=Station
BEGIN DESCRIPTION:
Brays Bayou Watershed
Keegans Bayou
HCFCD Unit D118-00-00
Flood Hazard & Floodway Model
10, 2, 1, 0.2% Event
Filename D118.prj
Prepared by: Dodson & Associates, Inc.   Date: December 2003
Reviewed by:____________________	 Date:_________
STATUS (Final RAS, SVSQ)
FOR FLOOD HARZARD RECOVERY DATA ONLY,03/02/2004
Will Be Voided Upon Release of The Preliminary DFIRM
END DESCRIPTION:
DSS Export Rating Curves= 0
DSS Export Rating Curve Sorted= 0
DSS Export Volume Flow Curves= 0
DXF OffsetX= 0
DXF OffsetY= 0
DXF ScaleX= 1
DXF ScaleY= 10

--- D118-00-00.p06 (plan) ---

Plan Title=Floodway
Version=Version 3.0.1  Mar 2001
Short Identifier=Floodway0607
Geom File=g03
Flow File=f05
Subcritical Flow
K Sum by GR= 0
Std Step Tol= 0.01
Critical Tol= 0.01
Num of Std Step Trials= 20
Max Error Tol= 0.3
Flow Tol Ratio= 0.001
Split Flow NTrial= 30
Split Flow Tol= 0.02
Split Flow Ratio= 0.02
Log Output Level= 0
Friction Slope Method= 1
Unsteady Friction Slope Method= 2
Parabolic Critical Depth
Global Vel Dist= 0 , 0 , 0
Global Log Level= 0
CheckData=True
Encroach Param=-1 ,0,0, 2
Encroach River=D118-00-00
Encroach Reach=Reach0
Encroach Node=35432
       1 2560.15 2694.94
Encroach Node=34220
       1 3067.07 3201.39
Encroach Node=33252
       1 3401.68 3541.42
Encroach Node=32996
       1 3515.08 3636.13
Encroach Node=32911
       1 3525.08 3647.52
Encroach Node=32841
       1 3525.08 3648.13
Encroach Node=32809
       1 3527.08 3648.13
Encroach Node=32728
       1 3530.08 3651.13
Encroach Node=32533
       1 3594.52 3724.64
Encroach Node=31640
       1 3447.64  3554.2
Encroach Node=30736
       1 3673.99 3782.72
Encroach Node=30553
       1 3769.38 3873.32
Encroach Node=30466
       1 3801.38 3905.32
Encroach Node=30425
       1 3801.38 3931.32
Encroach Node=30412
       1 3827.38 3931.32
Encroach Node=30376
       1 3833.38 3937.32
Encroach Node=30325
       1 3863.38 3967.32
Encroach Node=30151
       1 4190.96 4296.72
Encroach Node=29207
       1 4695.11 4805.16
Encroach Node=27995
       1  5022.6 5143.65
Encroach Node=26844
       1 4532.67 4654.68
Encroach Node=26387
       1 4123.78 4246.57
Encroach Node=26322
       1 4068.78 4191.57
Encroach Node=26246
       1  3951.8 4191.57
Encroach Node=26167
       1  3951.8 4074.59
Encroach Node=26111
       1 3892.98 4052.59
Encroach Node=25848
       1 3715.03 3860.37
Encroach Node=25367
       1 3645.54  3777.7
Encroach Node=24828
       1 3583.27 3739.63
Encroach Node=24790
       1 3583.27 3750.63
Encroach Node=24738
       1 3594.27 3750.63
Encroach Node=24703
       1 3598.84 3770.21
Encroach Node=24613
       1 3574.27 3772.26
Encroach Node=24205
       1 3802.13 3932.79
Encroach Node=23113
       1 4569.65 4693.81
Encroach Node=22141
       1 5386.27 5513.64
Encroach Node=21286
       1  5644.3 5824.82
Encroach Node=20173
       1 5774.04 5940.46
Encroach Node=20087
       1 5796.54  5938.6
Encroach Node=20024
       1 5760.06  5938.6
Encroach Node=19965
       1 5760.06 5885.92
Encroach Node=19879
       1 5719.61 5856.44
Encroach Node=19769
       1 5703.06 5833.25
Encroach Node=18896
       1 5748.72 5923.69
Encroach Node=17542
       1  5980.9 6174.24
Encroach Node=16500
       1 6259.31 6380.04
Encroach Node=15941
       1 6439.61 6563.75
Encroach Node=15759
       1 6420.15    6630
Encroach Node=15706
       1 6604.97    6860
Encroach Node=15660
       1 6604.97    6923
Encroach Node=15600
       1 6611.28    6923
Encroach Node=15530
       1 6661.61    6912
Encroach Node=15187
       1  6927.7    7178
Encroach Node=14737
       1    6986    7304
Encroach Node=14067
       1    7017    7328
Encroach Node=13929
       1    7012    7382
Encroach Node=13820
       1    7267    7622
Encroach Node=13681
       1 6982.65    7242
Encroach Node=13389
       1 6764.91    7242
Encroach Node=13135
       1 6764.91    6963
Encroach Node=12924
       1    4820    5160
Encroach Node=12881
       1    4820    5160
Encroach Node=12838
       1    4820    5160
Encroach Node=12790
       1    4740    5160
Encroach Node=12529
       1    4570    4990
Encroach Node=12370
       1    4460    4800
Encroach Node=11829
       1    4257    4577
Encroach Node=10872
       1    3900    4170
Encroach Node=10734
       1    3903 4117.43
Encroach Node=10710
       1 3923.55    4152
Encroach Node=10691
       1 3970.49    4152
Encroach Node=10376
       1 3913.55 4031.46
Encroach Node=10370
       1 3913.55 4246.46
Encroach Node=10330
       1 4128.55 4246.46
Encroach Node=10299
       1 1445.74 1593.65
Encroach Node=10089
       1 1604.15 1684.88
Encroach Node=9707
       1 1524.11 1598.77
Encroach Node=8916
       1 1367.01 1444.31
Encroach Node=7739
       1 1435.41 1538.15
Encroach Node=6574
       1 1667.79 1819.34
Encroach Node=5739
       1 1481.55 1772.44
Encroach Node=5477
       1 1628.52 1792.58
Encroach Node=4124
       1 2612.72 2723.97
Encroach Node=3724
       1 2576.86 2696.13
Encroach Node=2488
       1  2445.7 2585.32
Encroach Node=1825
       1 2398.67 2532.97
Encroach Node=1312
       1 2686.74 2838.22
Encroach Node=1208
       1 2692.72  2833.1
Encroach Node=1163
       1 2692.72  2833.1
Encroach Node=1087
       1 2695.72 2830.62
Encroach Node=1005
       1 2695.72 2830.62
Encroach Node=620
       1  2891.8 3002.27
Encroach Node=305
       1 3108.11  3265.8
Encroach Node=281
       1 3228.43 3381.28
Encroach Node=204
       1 3444.66 3595.94
Encroach Reach=D118-00-00_0002
Encroach Node=35432
       1 2560.15 2694.94
Encroach Node=34220
       1 3067.07 3201.39
Encroach Node=33252
       1 3401.68 3541.42
Encroach Node=32996
       1 3515.08 3636.13
Encroach Node=32911
       1 3525.08 3647.52
Encroach Node=32841
       1 3525.08 3648.13
Encroach Node=32809
       1 3527.08 3648.13
Encroach Node=32728
       1 3530.08 3651.13
Encroach Node=32533
       1 3594.52 3724.64
Encroach Node=31640
       1 3447.64  3554.2
Encroach Node=30736
       1 3673.99 3782.72
Encroach Node=30553
       1 3769.38 3873.32
Encroach Node=30466
       1 3801.38 3905.32
Encroach Node=30425
       1 3801.38 3931.32
Encroach Node=30412
       1 3827.38 3931.32
Encroach Node=30376
       1 3833.38 3937.32
Encroach Node=30325
       1 3863.38 3967.32
Encroach Node=30151
       1 4190.96 4296.72
Encroach Node=29207
       1 4695.11 4805.16
Encroach Node=27995
       1  5022.6 5143.65
Encroach Node=26844
       1 4532.67 4654.68
Encroach Node=26387
       1 4123.78 4246.57
Encroach Node=26322
       1 4068.78 4191.57
Encroach Node=26246
       1  3951.8 4191.57
Encroach Node=26167
       1  3951.8 4074.59
Encroach Node=26111
       1 3892.98 4052.59
Encroach Node=25848
       1 3715.03 3860.37
Encroach Node=25367
       1 3645.54  3777.7
Encroach Node=24828
       1 3583.27 3739.63
Encroach Node=24790
       1 3583.27 3750.63
Encroach Node=24738
       1 3594.27 3750.63
Encroach Node=24703
       1 3598.84 3770.21
Encroach Node=24613
       1 3574.27 3772.26
Encroach Node=24205
       1 3802.13 3932.79
Encroach Node=23113
       1 4569.65 4693.81
Encroach Node=22141
       1 5386.27 5513.64
Encroach Node=21286
       1  5644.3 5824.82
Encroach Node=20173
       1 5774.04 5940.46
Encroach Node=20087
       1 5796.54  5938.6
Encroach Node=20024
       1 5760.06  5938.6
Encroach Node=19965
       1 5760.06 5885.92
Encroach Node=19879
       1 5719.61 5856.44
Encroach Node=19769
       1 5703.06 5833.25
Encroach Node=18896
       1 5748.72 5923.69
Encroach Node=17542
       1  5980.9 6174.24
Encroach Node=16500
       1 6259.31 6380.04
Encroach Node=15941
       1 6439.61 6563.75
Encroach Node=15759
       1 6420.15    6630
Encroach Node=15706
       1 6604.97    6860
Encroach Node=15660
       1 6604.97    6923
Encroach Node=15600
       1 6611.28    6923
Encroach Node=15530
       1 6661.61    6912
Encroach Node=15187
       1  6927.7    7178
Encroach Node=14737
       1    6986    7304
Encroach Node=14067
       1    7017    7328
Encroach Node=13929
       1    7012    7382
Encroach Node=13820
       1    7267    7622
Encroach Node=13681
       1 6982.65    7242
Encroach Node=13389
       1 6764.91    7242
Encroach Node=13135
       1 6764.91    6963
Encroach Node=12924
       1    4820    5160
Encroach Node=12881
       1    4820    5160
Encroach Node=12838
       1    4820    5160
Encroach Node=12790
       1    4740    5160
Encroach Node=12529
       1    4570    4990
Encroach Node=12370
       1    4460    4800
Encroach Node=11829
       1    4257    4577
Encroach Node=10872
       1    3900    4170
Encroach Node=10734
       1    3903 4117.43
Encroach Node=10710
       1 3923.55    4152
Encroach Node=10691
       1 3970.49    4152
Encroach Node=10376
       1 3913.55 4031.46
Encroach Node=10370
       1 3913.55 4246.46
Encroach Node=10330
       1 4128.55 4246.46
Encroach Node=10299
       1 1445.74 1593.65
Encroach Node=10089
       1 1604.15 1684.88
Encroach Node=9707
       1 1524.11 1598.77
Encroach Node=8916
       1 1367.01 1444.31
Encroach Node=7739
       1 1435.41 1538.15
Encroach Node=6574
       1 1667.79 1819.34
Encroach Node=5739
       1 1481.55 1772.44
Encroach Node=5477
       1 1628.52 1792.58
Encroach Node=4124
       1 2612.72 2723.97
Encroach Node=3724
       1 2576.86 2696.13
Encroach Node=2488
       1  2445.7 2585.32
Encroach Node=1825
       1 2398.67 2532.97
Encroach Node=1312
       1 2686.74 2838.22
Encroach Node=1208
       1 2692.72  2833.1
Encroach Node=1163
       1 2692.72  2833.1
Encroach Node=1087
       1 2695.72 2830.62
Encroach Node=1005
       1 2695.72 2830.62
Encroach Node=620
       1  2891.8 3002.27
Encroach Node=305
       1 3108.11  3265.8
Encroach Node=281
       1 3228.43 3381.28
Encroach Node=204
       1 3444.66 3595.94
Computation Interval=1HOUR
Output Interval=1HOUR
Run HTab= 0
Run UNet= 0
Run PostProcess= 0
UNET Theta= 1
UNET ZTol= 0.02
UNET ZSATol= 0.1
UNET MxIter= 20
UNET MaxInSteps= 20
UNET DtIC= 0
UNET DtMin= 0
UNET MaxCRTS= 20
UNET WFStab= 2
UNET SFStab= 1
UNET WFX= 1
UNET SFX= 1
UNET Convert EG Bridges=-1
UNET Use Existing IB Tables=-1
Instantaneous Interval=1HOUR
Write IC File= 0
Write Velocity= 0
Write Detailed= 0

--- D118-00-00.p01 (plan) ---

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Plan Title=Storage Routing
Short Identifier=Store_Rout
Geom File=g03
Flow File=f02
Encroach Param=-1 ,0,0, 0

--- D118-00-00.p05 (plan) ---

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Plan Title=FEMA Effective June 2007
Short Identifier=FEMAeff0607
Geom File=g03
Flow File=f04
Encroach Param=-1 ,0,0, 0

--- D118-00-00.f05 (steady flow) ---

Flow Title=Floodway
Version=Version 3.0.1  Mar 2001
Number of Profiles= 2
Profile Names=1PCT_100yr,1PCTFloodway_100yrFW
River Rch & RM=D118-00-00,D118-00-00_0002 ,35432
    2128    2128
River Rch & RM=D118-00-00,D118-00-00_0002 ,33252
    2128    2128
River Rch & RM=D118-00-00,D118-00-00_0002 ,32728
    2225    2225
River Rch & RM=D118-00-00,D118-00-00_0002 ,31640
    2349    2349
River Rch & RM=D118-00-00,D118-00-00_0002 ,30325
    2459    2459
River Rch & RM=D118-00-00,D118-00-00_0002 ,29207
    2585    2585
River Rch & RM=D118-00-00,D118-00-00_0002 ,27995
    2793    2793
River Rch & RM=D118-00-00,D118-00-00_0002 ,26111
    2970    2970
River Rch & RM=D118-00-00,D118-00-00_0002 ,24613
    1593    1593
River Rch & RM=D118-00-00,D118-00-00_0002 ,23113
    1978    1978
River Rch & RM=D118-00-00,D118-00-00_0002 ,21286
    2368    2368
River Rch & RM=D118-00-00,D118-00-00_0002 ,19769
    2626    2626
River Rch & RM=D118-00-00,D118-00-00_0002 ,18896
    3082    3082
River Rch & RM=D118-00-00,D118-00-00_0002 ,17542
    3487    3487
River Rch & RM=D118-00-00,D118-00-00_0002 ,16500
    3912    3912
River Rch & RM=D118-00-00,D118-00-00_0002 ,15530
    4652    4652
River Rch & RM=D118-00-00,D118-00-00_0002 ,14067
    5687    5687
River Rch & RM=D118-00-00,D118-00-00_0002 ,12370
    4966    4966
River Rch & RM=D118-00-00,D118-00-00_0002 ,10872
    6331    6331
River Rch & RM=D118-00-00,D118-00-00_0002 ,8916
    6253    6253
River Rch & RM=D118-00-00,D118-00-00_0002 ,6574
    6830    6830
River Rch & RM=D118-00-00,D118-00-00_0002 ,4124
    7643    7643
River Rch & RM=D118-00-00,D118-00-00_0002 ,1005
    7925    7925
Boundary for River Rch & Prof#=D118-00-00,D118-00-00_0002 , 1
Up Type= 0
Dn Type= 1
Dn Known WS=59.69
Boundary for River Rch & Prof#=D118-00-00,D118-00-00_0002 , 2
Up Type= 0
Dn Type= 1
Dn Known WS=59.69
DSS Import GetInterval= 0
DSS Import GetPeak= 0
DSS Import FillOption= 0

--- D118-00-00.f02 (steady flow) ---

Flow Title=Storage Routing
Version=Version 3.0.1  Mar 2001
Number of Profiles= 8
Profile Names=.1,.2,.4,.6,.8,1.0,1.2,1.5
River Rch & RM=D118-00-00,D118-00-00_0002 ,35432
     213     426     852    1278    1704    2130    2556    3195
River Rch & RM=D118-00-00,D118-00-00_0002 ,33252
     213     426     852    1278    1704    2130    2556    3195
River Rch & RM=D118-00-00,D118-00-00_0002 ,32728
     134     268     536     804    1072    1340    1608    2010
River Rch & RM=D118-00-00,D118-00-00_0002 ,24613
     412     824    1648    2472    3296    4120    4944    6180
River Rch & RM=D118-00-00,D118-00-00_0002 ,12370
     574    1148    2296    3444    4592    5740    6888    8610
River Rch & RM=D118-00-00,D118-00-00_0002 ,8916
     792    1584    3168    4752    6336    7920    9504   11880
Boundary for River Rch & Prof#=D118-00-00,D118-00-00_0002 , 1
Up Type= 0
Dn Type= 3
Dn Slope=.0008
Boundary for River Rch & Prof#=D118-00-00,D118-00-00_0002 , 2
Up Type= 0
Dn Type= 3
Dn Slope=.0008
Boundary for River Rch & Prof#=D118-00-00,D118-00-00_0002 , 3
Up Type= 0
Dn Type= 3
Dn Slope=.0008
Boundary for River Rch & Prof#=D118-00-00,D118-00-00_0002 , 4
Up Type= 0
Dn Type= 3
Dn Slope=.0008
DSS Import GetInterval= 0
DSS Import GetPeak= 0
DSS Import FillOption= 0

--- D118-00-00.f04 (steady flow) ---

Flow Title=FEMA Effective June 2007
Version=Version 3.0.1  Mar 2001
Number of Profiles= 4
Profile Names=10PCT_10yr,2PCT_50yr,1PCT_100yr,0.2PCT_500yr
River Rch & RM=D118-00-00,D118-00-00_0002 ,35432
     966    1707    2128    3454
River Rch & RM=D118-00-00,D118-00-00_0002 ,33252
     966    1707    2128    3454
River Rch & RM=D118-00-00,D118-00-00_0002 ,32728
    1044    1807    2225    3522
River Rch & RM=D118-00-00,D118-00-00_0002 ,31640
    1146    1937    2349    3606
River Rch & RM=D118-00-00,D118-00-00_0002 ,30325
    1240    2054    2459    3679
River Rch & RM=D118-00-00,D118-00-00_0002 ,29207
    1352    2189    2585    3761
River Rch & RM=D118-00-00,D118-00-00_0002 ,27995
    1545    2417    2793    3890
River Rch & RM=D118-00-00,D118-00-00_0002 ,26111
    1718    2615    2970    3996
River Rch & RM=D118-00-00,D118-00-00_0002 ,24613
    1310    1493    1593    1873
River Rch & RM=D118-00-00,D118-00-00_0002 ,23113
    1555    1833    1978    2380
River Rch & RM=D118-00-00,D118-00-00_0002 ,21286
    1792    2173    2368    2903
River Rch & RM=D118-00-00,D118-00-00_0002 ,19769
    1945    2397    2626    3254
River Rch & RM=D118-00-00,D118-00-00_0002 ,18896
    2209    2792    3082    3886
River Rch & RM=D118-00-00,D118-00-00_0002 ,17542
    2435    3138    3487    4454
River Rch & RM=D118-00-00,D118-00-00_0002 ,16500
    2667    3500    3912    5057
River Rch & RM=D118-00-00,D118-00-00_0002 ,15530
    3059    4125    4652    6125
River Rch & RM=D118-00-00,D118-00-00_0002 ,14067
    3587    4992    5687    7650
River Rch & RM=D118-00-00,D118-00-00_0002 ,12370
    3474    4478    4966    6265
River Rch & RM=D118-00-00,D118-00-00_0002 ,10872
    4296    5668    6331    7955
River Rch & RM=D118-00-00,D118-00-00_0002 ,8916
    4509    5721    6253    7323
River Rch & RM=D118-00-00,D118-00-00_0002 ,6574
    4842    6237    6830    8117
River Rch & RM=D118-00-00,D118-00-00_0002 ,4124
    5303    6961    7643    9253
River Rch & RM=D118-00-00,D118-00-00_0002 ,1005
    5461    7212    7925    9652
Boundary for River Rch & Prof#=D118-00-00,D118-00-00_0002 , 1
Up Type= 0
Dn Type= 3
Dn Slope=.0008
Boundary for River Rch & Prof#=D118-00-00,D118-00-00_0002 , 2
Up Type= 0
Dn Type= 3
Dn Slope=.0008
Boundary for River Rch & Prof#=D118-00-00,D118-00-00_0002 , 3
Up Type= 0
Dn Type= 3
Dn Slope=.0008
Boundary for River Rch & Prof#=D118-00-00,D118-00-00_0002 , 4
Up Type= 0
Dn Type= 3
Dn Slope=.0008
DSS Import GetInterval= 0
DSS Import GetPeak= 0
DSS Import FillOption= 0

--- D118-00-00.g03 (geometry) ---

Geom Title=D118-00-00 June 2007
Version=Version 3.0.1  Mar 2001

River Reach=D118-00-00      ,D118-00-00_0002
Reach XY= 30
      3040291.96    13807931.875        3041325.       13807954.
     3043429.666    13806974.283       3044504.5    13806895.048
     3045599.203    13805996.624     3046215.088    13804999.301
     3046912.543    13804645.475     3047522.305    13804597.245
     3048590.249    13805482.605     3049329.861    13805334.223
     3050047.477    13805424.041     3050889.109    13804820.676
     3051179.374    13804478.311     3051344.975    13803875.452
     3051985.048    13803261.428      3052724.21     13803059.21
     3053979.694    13803240.961     3058854.668    13801744.976
     3061338.672    13802500.411     3063300.323    13804073.608
      3063913.53    13804359.541     3064109.894    13804793.609
     3064771.621    13805198.393     3064842.327    13805471.913
     3065173.528     13805630.07      3066087.12    13806685.074
     3067689.163    13807014.414     3068633.155    13808142.132
      3069659.76    13808624.429      3070339.22    13808704.282

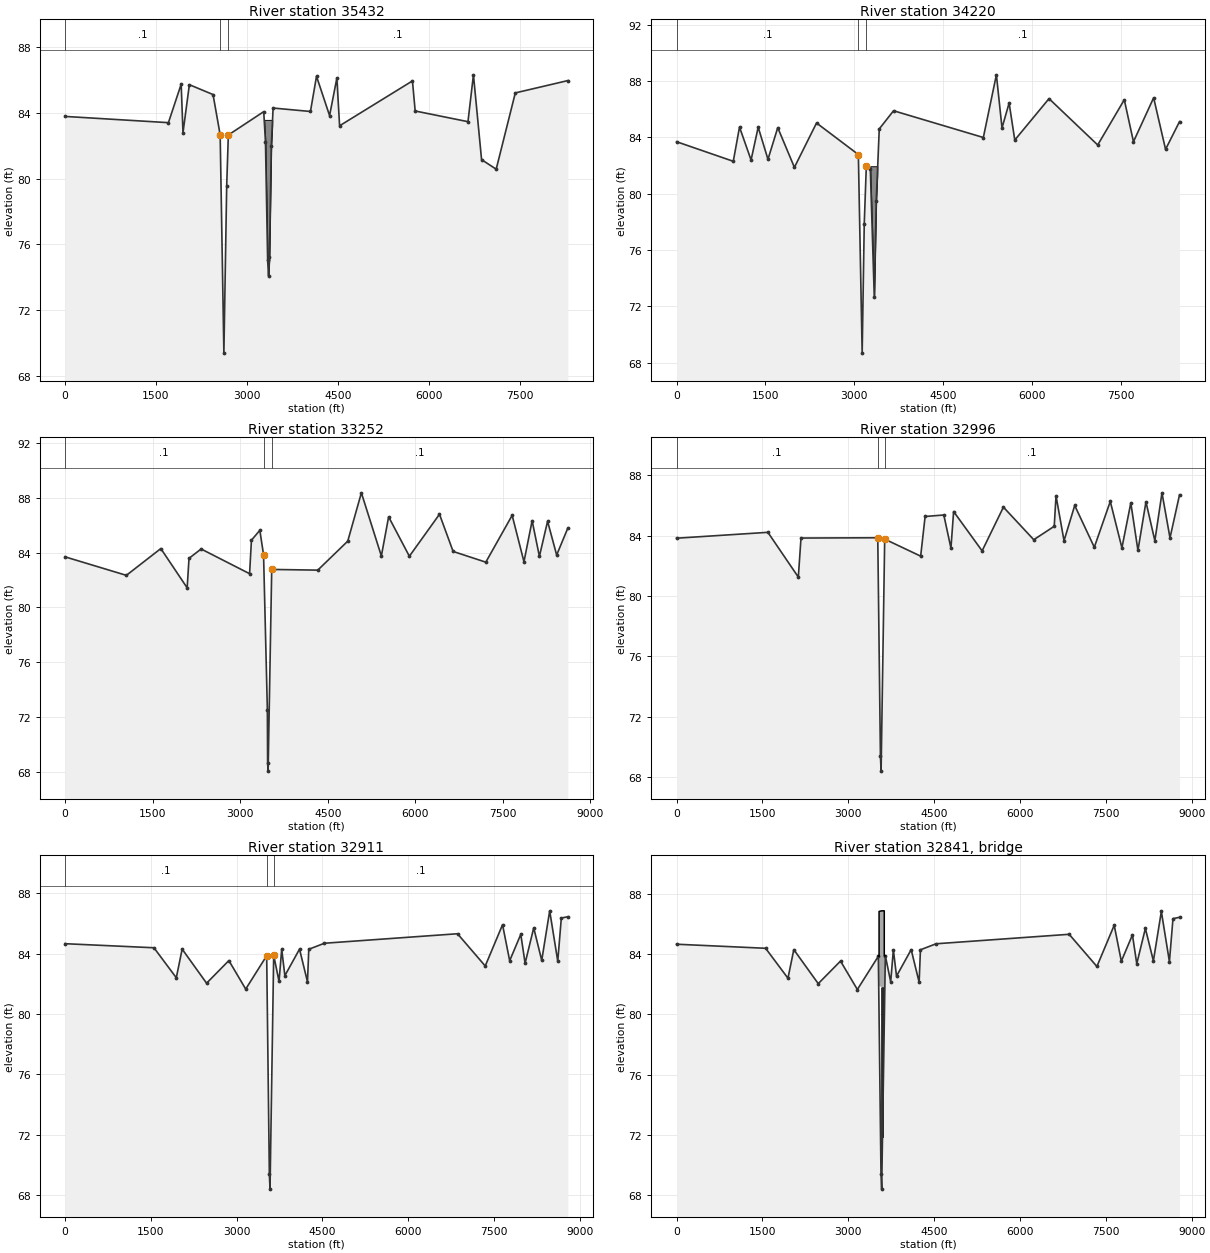
Type RM Length L Ch R = 1 ,35432   ,1348.02,1211.98,1034.39
BEGIN DESCRIPTION:
Added Section to Meet Limit of Detailed Study
END DESCRIPTION:
XS GIS Cut Line= 6
      3040598.11    13810548.478     3040648.094    13810198.741
     3040710.573     13808549.98     3040679.334    13807950.431
     3040698.077    13807282.183     3040936.841    13802265.133
#Sta/Elev= 30
       0   83.78 1706.88    83.4 1917.03   85.74 1947.05   82.79 2052.16   85.71
 2442.69   85.11 2560.15   82.66 2621.57   69.38 2667.93   79.57 2694.94   82.65
 3278.66   84.07  3307.2   82.23 3343.27   75.03 3358.29   74.08 3373.31   75.23
 3403.35   81.98 3433.39   84.29 4049.24   84.08 4149.21   86.22 4364.67   83.83
 4484.83   86.11  4529.9   83.21 5731.46   85.94 5776.51   84.11 6647.33   83.46
 6737.42   86.31 6871.54   81.15 7112.77   80.57 7428.07   85.21 8294.88   85.96
#Mann= 3 , 0 , 0
       0      .1       0 2560.15     .04       0 2694.94      .1       0
#XS Ineff= 2 , 0
       0    2550            2700       0
Permanent Ineff=
       T       T
#Block Obstruct= 1 ,-1
 3284.41 3419.49   83.57
Bank Sta=2560.15,2694.94
XS Rating Curve= 0
Exp/Cntr=.3,.1

Type RM Length L Ch R = 1 ,34220   ,920.04,968.14,917.36
BEGIN DESCRIPTION:
Added Section to Meet Limit of Detailed Study
END DESCRIPTION:
XS GIS Cut Line= 6
      3042266.29    13810642.158     3042335.022    13808599.943
     3041807.329    13807654.794     3041672.746    13807382.108
     3041710.234    13804996.402     3041053.541    13802407.709
#Sta/Elev= 30
       0   83.69  956.58    82.3 1061.64   84.73 1256.75   82.39 1376.82   84.72
 1541.91   82.44    1707   84.69  1987.9   81.87 2361.53   85.02 3067.07   82.78
 3131.57   68.68 3166.49   77.85 3201.39   81.95 3269.18   81.76 3335.56   72.69
 3368.59   79.45 3419.89    84.6 3660.96   85.89 5176.14   83.99 5396.42   88.44
 5491.18   84.67  5611.2   86.44 5706.59   83.81 6284.48   86.75 7105.82   83.46
  7554.6   86.67 7709.35   83.69 8049.81   86.81 8250.98   83.15 8486.63   85.12
#Mann= 3 , 0 , 0
       0      .1       0 3067.07     .04       0 3201.39      .1       0
#XS Ineff= 2 , 0
       0    3060            3210       0
Permanent Ineff=
       T       T
#Block Obstruct= 1 ,-1
 3269.93 3387.62   81.95
Bank Sta=3067.07,3201.39
XS Rating Curve= 0
Exp/Cntr=.3,.1

Type RM Length L Ch R = 1 ,33252   ,165.74,255.52,286.91
BEGIN DESCRIPTION:
Surveyed Cross-Section
END DESCRIPTION:
XS GIS Cut Line= 5
      3043125.62    13810723.433     3043208.171    13808641.728
     3042756.874    13807398.423     3042629.372    13807328.452
     3041288.283    13802447.378
#Sta/Elev= 30
       0   83.69 1051.96   82.34 1642.22   84.29 2093.16   81.43 2125.07   83.58
 2332.52   84.26 3162.32   82.46 3194.23    84.9 3337.85   85.62 3401.68   83.84
  3466.7   72.56 3471.35   68.64 3479.57   68.08 3541.42   82.77 4330.24   82.72
 4843.58   84.83 5076.92   88.35 5419.15   83.75  5543.6    86.6 5898.72   83.73
 6414.73   86.79 6648.06   84.08 7208.08    83.3  7659.2   86.71 7861.42   83.33
 8001.43   86.32 8125.87   83.72 8265.88   86.28 8421.43   83.82 8613.42   85.79
#Mann= 3 , 0 , 0
       0      .1       0 3401.68     .04       0 3541.42      .1       0
#XS Ineff= 2 , 0
       0    3368            3557       0
Permanent Ineff=
       T       T
Bank Sta=3401.68,3541.42
XS Rating Curve= 0
Exp/Cntr=.3,.1

Type RM Length L Ch R = 1 ,32996   ,87.41,85.61,88.08
BEGIN DESCRIPTION:
Copied cross-section 32809/XS1
END DESCRIPTION:
XS GIS Cut Line= 5
     3043250.156    13810765.571     3043353.691    13808809.768
     3042936.734     13807315.31     3042886.315    13807186.798
     3041521.132    13802232.021
#Sta/Elev= 30
       0   83.84  1595.3   84.23 2127.01   81.26 2173.73   83.85 3515.08   83.87
 3561.53   69.39 3573.26   68.39 3636.13   83.78 4264.57   82.65 4342.36   85.28
  4669.1   85.38 4793.57   83.18 4840.25   85.61 5338.13      83 5710.54    85.9
 6240.55   83.74 6598.41   84.63 6629.53   86.65 6769.56   83.67 6956.26   86.01
 7298.56   83.24  7577.7   86.28 7780.89    83.2 7936.48   86.18 8060.95   83.03
 8200.98   86.25 8356.57   83.67 8480.98   86.85 8621.07   83.86 8787.53   86.72
#Mann= 3 , 0 , 0
       0      .1       0 3515.08     .04       0 3636.13      .1       0
#XS Ineff= 2 , 0
       0    3496            3636       0
Permanent Ineff=
       T       T
Bank Sta=3515.08,3636.13
XS Rating Curve= 0
Exp/Cntr=.5,.3

Type RM Length L Ch R = 1 ,32911   ,102.25,102.24,104.87
BEGIN DESCRIPTION:
Copied cross-section 32809/XS2
END DESCRIPTION:
XS GIS Cut Line= 5
     3043338.024    13810755.711     3043441.559    13808799.908
     3043024.602     13807305.45     3042974.183    13807176.938
        3041609.    13802222.161
#Sta/Elev= 30
       0   84.67 1555.39    84.4 1945.93   82.41 2048.07   84.31 2474.94   82.05
 2864.27   83.55 3158.51   81.66 3525.08   83.87 3571.53   69.39 3583.26   68.39
 3647.52    83.9  3740.9   82.17 3787.57    84.3 3842.69   82.55 4098.75   84.31
 4237.98   82.14 4260.57    84.3 4534.41    84.7  6859.2   85.33  7343.8   83.19
 7646.19   85.93 7770.67   83.54 7964.96   85.29 8040.39   83.37 8190.84   85.72
 8330.79   83.56 8469.92   86.85 8610.85   83.51 8673.08   86.37 8787.54   86.46
#Mann= 3 , 0 , 0
       0      .1       0 3525.08     .04       0 3647.52      .1       0
#XS Ineff= 2 , 0
       0    3512            3682       0
Permanent Ineff=
       T       T
Bank Sta=3525.08,3647.52
XS Rating Curve= 0
Exp/Cntr=.5,.3

Type RM Length L Ch R = 3 ,32841   ,,,
BEGIN DESCRIPTION:
Synott bridge
END DESCRIPTION:
Bridge Culvert--1,0,-1,-1, 0
Deck Dist Width WeirC Skew NumUp NumDn MinLoCord MaxHiCord MaxSubmerge Is_Ogee
8.62,85,2.6,0, 7, 7, , , .95, 0, 0,0,,
 3525.08 3537.76 3537.76 3583.26 3628.76 3628.76 3647.52
   83.87   83.87   86.85   86.89   86.89    83.9    83.9
     -.3     -.3   81.89   81.83   81.83     -.3     -.3
 3527.08 3539.76 3539.76 3585.26 3630.76 3630.76 3648.13
   83.87   83.87   86.85   86.89   86.89   83.78   83.78
     -.3     -.3   81.89   81.83   81.83     -.3     -.3
Pier Skew, UpSta & Num, DnSta & Num=  ,3567.49, 2 ,3569.49, 2 , 0 , 0 , 0 ,,
     1.4     1.4
       0      83
     1.4     1.4
       0      83
Pier Skew, UpSta & Num, DnSta & Num=  ,3597.49, 2 ,3599.49, 2 , 0 , 0 , 0 ,,
     1.4     1.4
       0      83
     1.4     1.4
       0      83
BR Coef=-1 , 1 , 1 ,1.25, 0 ,,,.8,-1,2,0,
WSPro=,,,, 1 ,,,, 0 ,,,, 0 ,,,,-1 ,-1 ,-1 , 0 , 0 , 0 , 0 , 0
BC Design=,, 0 ,, 0 ,,,,,,

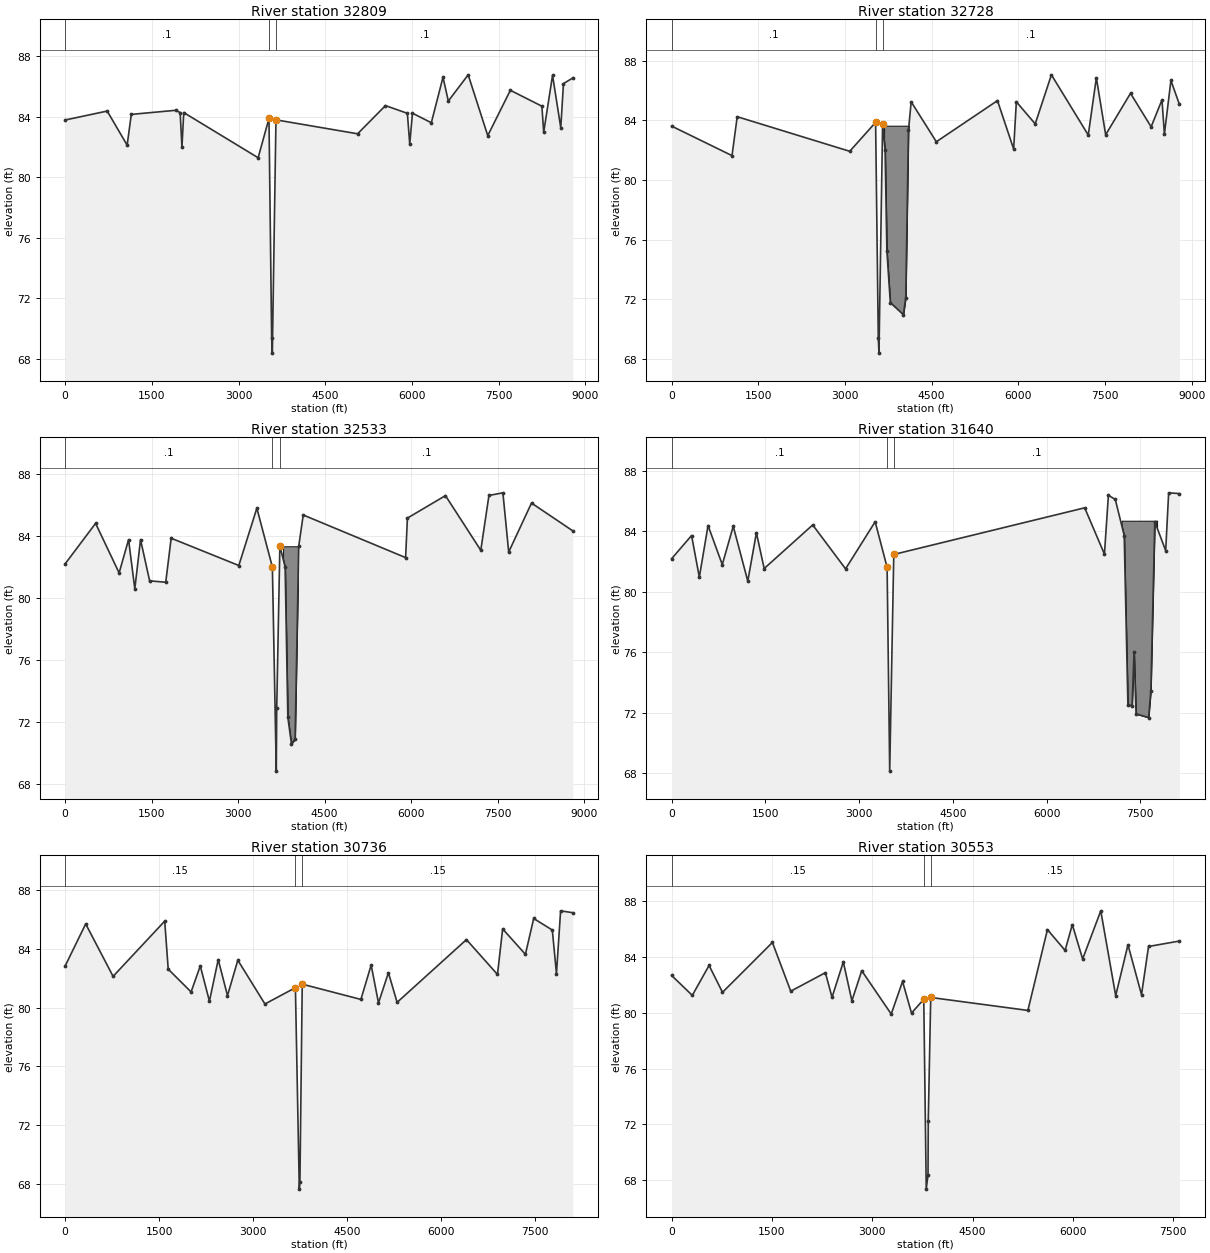
Type RM Length L Ch R = 1 ,32809   ,76.73,80.23,78.63
BEGIN DESCRIPTION:
Surveyed Cross-Section/XS3
END DESCRIPTION:
XS GIS Cut Line= 5
     3043435.021    13810723.433     3043538.557     13808767.63
       3043121.6    13807273.172     3043071.181     13807144.66
     3041705.997    13802189.883
#Sta/Elev= 30
       0   83.77  726.95   84.36 1072.43   82.11 1144.51   84.14 1913.61   84.41
 1989.82   84.26 2020.97   81.99 2052.11   84.26 3339.55   81.28 3527.08   83.87
 3573.53   69.39 3585.26   68.39 3648.13   83.78 5061.04   82.86 5543.37   84.72
 5922.43   84.21 5963.46   82.17 6010.14   84.22 6336.88   83.59 6539.14   86.59
 6631.15   85.02 6974.77   86.75 7313.67   82.74 7704.97   85.73 8250.63   84.68
 8281.75   82.96 8435.16   86.72 8577.37   83.26 8624.05   86.17 8787.54   86.55
#Mann= 3 , 0 , 0
       0      .1       0 3527.08     .04       0 3648.13      .1       0
#XS Ineff= 2 , 0
       0    3493            3771       0
Permanent Ineff=
       T       T
Bank Sta=3527.08,3648.13
XS Rating Curve= 0
Exp/Cntr=.5,.3

Type RM Length L Ch R = 1 ,32728   ,195.88,195.73,186.49
BEGIN DESCRIPTION:
Copied cross-section 32809/XS4
END DESCRIPTION:
XS GIS Cut Line= 5
     3043502.652    13810680.741     3043606.187    13808724.938
      3043189.23     13807230.48     3043138.811    13807101.968
     3041773.628    13802147.191
#Sta/Elev= 30
       0   83.62  1044.7   81.64 1134.83   84.25 3082.32   81.93 3530.08   83.87
 3576.53   69.39 3588.26   68.39 3651.13   83.78 3694.25      82 3725.37   75.23
 3784.82   71.78  4010.7   70.97 4052.11   72.12 4098.78   83.33 4145.46   85.25
 4581.11   82.57 5639.12   85.33 5919.18   82.08 5965.86   85.25  6292.6   83.77
 6572.66   87.06 7210.57   83.02  7350.6   86.86  7511.8   83.04 7941.84   85.82
 8298.68   83.57  8486.4   85.38 8528.25   83.08 8641.19   86.68 8787.53   85.08
#Mann= 3 , 0 , 0
       0      .1       0 3530.08     .04       0 3651.13      .1       0
#XS Ineff= 2 , 0
       0    3451            3826       0
Permanent Ineff=
       T       T
#Block Obstruct= 1 ,-1
 3677.42 4129.03   83.65
Bank Sta=3530.08,3651.13
XS Rating Curve= 0
Exp/Cntr=.3,.1

Type RM Length L Ch R = 1 ,32533   ,806.26,892.35,927.57
BEGIN DESCRIPTION:
Surveyed Cross-Section
END DESCRIPTION:
XS GIS Cut Line= 5
     3044127.864    13810596.001     3043937.122    13809086.041
     3043352.848    13807121.528     3043295.957    13806979.364
     3041780.385     13802126.94
#Sta/Elev= 30
       0   82.18  527.66   84.79  935.88   81.59 1099.62   83.74 1208.03   80.56
 1307.28   83.74 1465.05   81.08 1744.74   80.99 1838.64   83.83 3012.34   82.07
 3325.33   85.77 3594.52   81.97 3662.19    68.8 3669.96   72.88 3724.64   83.34
 3815.65   81.97 3862.79   72.27 3925.65   70.56 3988.51   70.86 4051.36   83.31
 4129.94   85.33 5905.69   82.58 5937.12   85.13 6597.13   86.58    7210   83.05
 7351.43   86.59 7593.62   86.76 7694.25   82.94 8090.02    86.1 8808.25    84.3
#Mann= 3 , 0 , 0
       0      .1       0 3594.52     .04       0 3724.64      .1       0
#XS Ineff= 2 , 0
       0    3383            3951       0
Permanent Ineff=
       T       T
#Block Obstruct= 1 ,-1
 3780.65 4038.71   83.31
Bank Sta=3594.52,3724.64
XS Rating Curve= 0
Exp/Cntr=.3,.1

Type RM Length L Ch R = 1 ,31640   ,1061.46,904.02,784.18
BEGIN DESCRIPTION:
Surveyed Cross-Section
END DESCRIPTION:
XS GIS Cut Line= 6
     3045023.261    13810337.666     3045024.673    13810286.537
     3044171.642    13807029.849     3044195.336    13806866.696
     3043644.275    13804736.471     3042906.556     13802514.55
#Sta/Elev= 30
       0   82.18  318.92   83.71  442.97   80.96  582.53   84.37  810.08   81.79
  985.68   84.32 1218.27    80.7 1356.31   83.89 1480.49   81.53 2257.18   84.41
 2782.86   81.51 3256.45   84.62 3447.64   81.61  3489.1   68.15  3554.2   82.46
 6608.97   85.54 6925.07   82.48 6988.29   86.37 7098.93   86.09 7241.17   83.71
 7300.69   72.51 7367.61   72.48 7399.23   76.05 7430.84   71.93 7631.94   71.69
 7667.91   73.46 7731.13   84.62 7904.99   82.71 7952.41   86.53  8124.1   86.48
#Mann= 3 , 0 , 0
       0      .1       0 3447.64     .04       0  3554.2      .1       0
#XS Ineff= 2 , 0
       0    3203            3648       0
Permanent Ineff=
       T       T
#Block Obstruct= 1 ,-1
    7200 7767.74   84.69
Bank Sta=3447.64,3554.2
XS Rating Curve= 0
Exp/Cntr=.3,.1

Type RM Length L Ch R = 1 ,30736   ,224.51,183.15,303.81
BEGIN DESCRIPTION:
Surveyed Cross-Section
END DESCRIPTION:
XS GIS Cut Line= 5
     3046555.414    13809895.616     3046552.686    13809872.212
     3045003.588    13806601.155     3044916.755      13806457.4
     3043122.488    13802559.007
#Sta/Elev= 30
       0   82.83  327.34   85.69  764.58   82.12 1588.46   85.88 1644.22   82.61
 2009.36   81.06 2155.96   82.83    2302   80.43 2442.18   83.26 2590.25   80.81
 2754.99   83.22 3187.75   80.24 3673.99   81.35 3736.02   67.64 3746.13   68.15
 3782.72   81.59 4718.92   80.55 4882.92   82.89 4999.63   80.31 5158.26   82.37
 5296.85   80.35 6403.19   84.62 6898.57   82.25 6981.13   85.35 7344.41   83.62
 7476.51   86.06 7773.73   85.27 7839.78    82.3 7905.83   86.58 8102.32   86.45
#Mann= 3 , 0 , 0
       0     .15       0 3673.99     .04       0 3782.72     .15       0
#XS Ineff= 2 , 0
       0    3469            3816       0
Permanent Ineff=
       T       T
Bank Sta=3673.99,3782.72
XS Rating Curve= 0
Exp/Cntr=.3,.1

Type RM Length L Ch R = 1 ,30553   ,98.51,86.68,108.44
BEGIN DESCRIPTION:
Copied cross-section 30376/XS1
END DESCRIPTION:
XS GIS Cut Line= 6
     3046797.353    13809825.813     3046798.127    13809810.976
     3045151.362    13806472.485      3045063.09    13806366.397
      3044309.97    13803289.515      3044268.89    13802743.552
#Sta/Elev= 30
       0   82.68  308.64   81.25  559.53    83.4  760.23   81.47 1506.42   85.05
 1780.49   81.55 2298.58   82.88  2397.6   81.11  2566.6   83.65 2694.66   80.86
 2841.93   83.02 3282.73   79.91 3452.27   82.25 3585.84   79.98 3769.38   80.97
 3806.17   67.34 3832.68   68.37  3836.4   72.26 3873.32    81.1  5325.9   80.17
 5617.98   85.97 5881.84   84.48 5989.94   86.33 6144.37   83.86 6415.44   87.32
 6638.54   81.23 6822.18   84.88 7024.61    81.3 7129.39   84.76 7590.63   85.15
#Mann= 3 , 0 , 0
       0     .15       0 3769.38     .04       0 3873.32     .15       0
#XS Ineff= 2 , 0
       0    3557            3910       0
Permanent Ineff=
       T       T
Bank Sta=3769.38,3873.32
XS Rating Curve= 0
Exp/Cntr=.5,.3

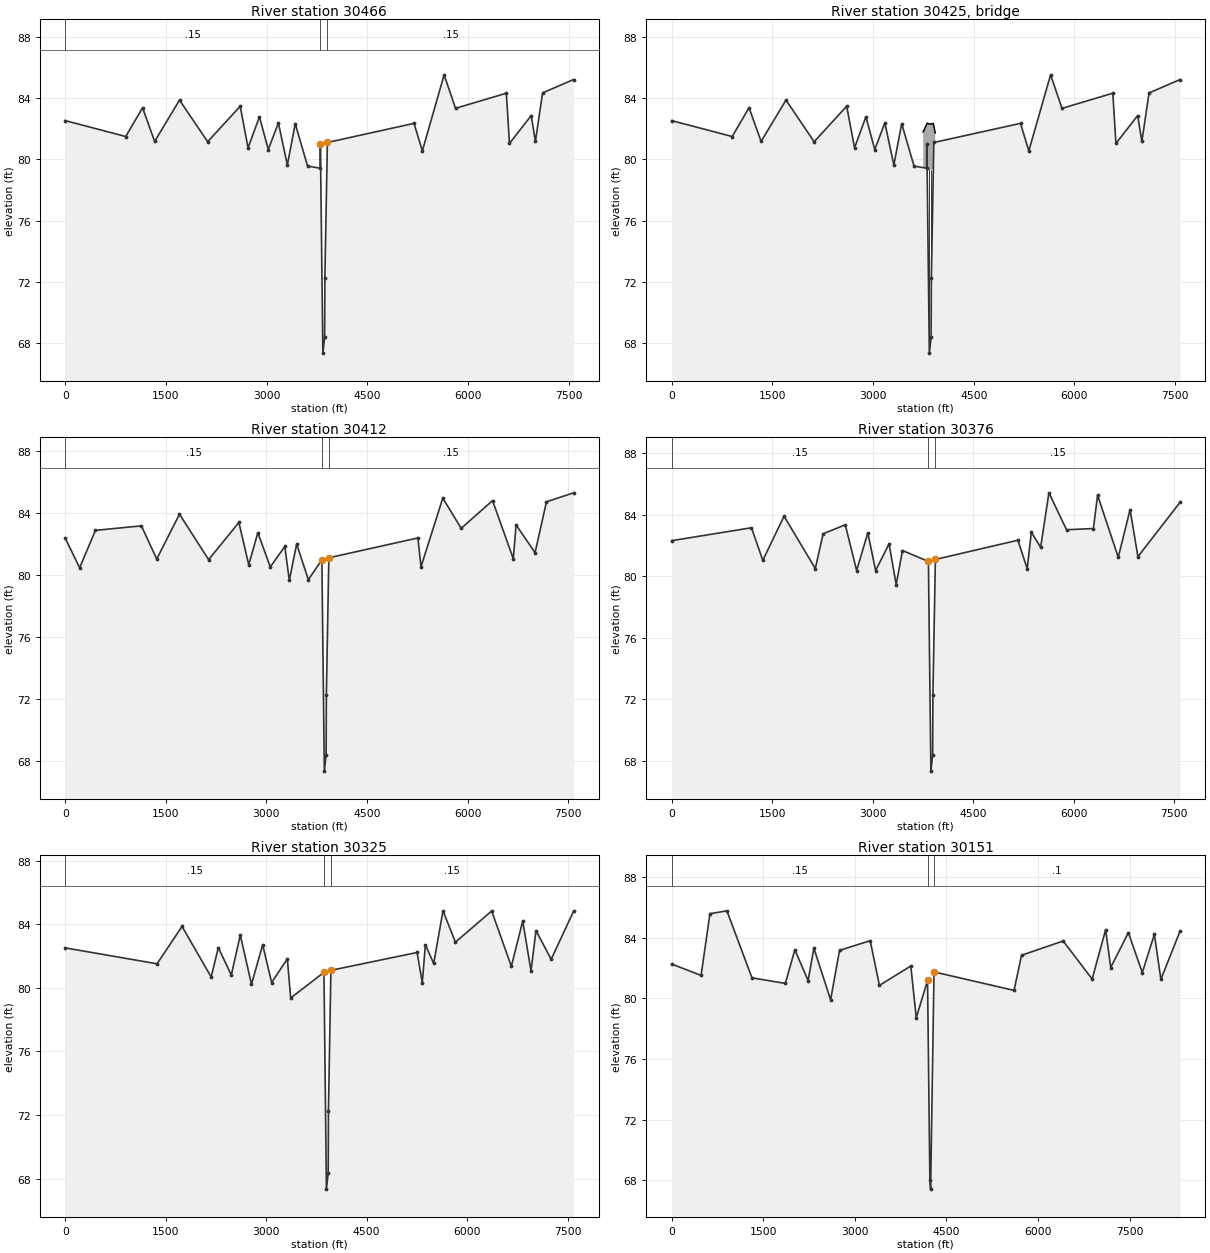
Type RM Length L Ch R = 1 ,30466   ,61.54,54.81,67.31
BEGIN DESCRIPTION:
Copied cross-section 30376/XS2
END DESCRIPTION:
XS GIS Cut Line= 6
     3046873.331    13809803.892     3046874.871    13809777.965
     3045220.362    13806419.885      3045132.09    13806313.797
     3044318.693    13803022.212     3044288.669    13802749.636
#Sta/Elev= 30
       0   82.53   901.6   81.49 1152.43   83.37 1332.35   81.17 1702.85   83.87
 2122.29   81.15 2607.22   83.47 2723.87   80.75 2893.56   82.78 3025.27   80.64
 3175.76   82.38 3309.54   79.63 3426.59   82.33 3610.53   79.56 3798.64   79.42
 3801.38   80.97 3838.17   67.34 3864.68   68.37  3868.4   72.26 3905.32    81.1
 5196.46   82.35 5320.07   80.55 5644.55   85.52 5814.51   83.33 6571.62   84.32
 6617.97   81.04 6942.45   82.86 7004.25   81.17 7111.39   84.34 7572.35   85.21
#Mann= 3 , 0 , 0
       0     .15       0 3801.38     .04       0 3905.32     .15       0
#XS Ineff= 2 , 0
       0    3591            3950       0
Permanent Ineff=
       T       T
Bank Sta=3801.38,3905.32
XS Rating Curve= 0
Exp/Cntr=.5,.3

Type RM Length L Ch R = 3 ,30425   ,,,
BEGIN DESCRIPTION:
Huntington Bridge
END DESCRIPTION:
Bridge Culvert--1,0,-1,-1, 0
Deck Dist Width WeirC Skew NumUp NumDn MinLoCord MaxHiCord MaxSubmerge Is_Ogee
4.805,45.2,2.6,0, 5, 5, , , .95, 0, 0,0,,
 3746.49 3805.32 3851.14 3896.97 3926.66
   81.79   82.36    82.3   82.34   81.72
     -.3   79.38   79.32   79.36     -.3
 3787.96 3831.61 3877.43 3923.26 3945.03
   81.79   82.36    82.3   82.34    81.8
     -.3   79.38   79.32   79.36     -.3
Pier Skew, UpSta & Num, DnSta & Num=  ,3835.73, 2 ,3862.02, 2 , 0 , 0 , 0 ,,
     1.2     1.2
       0      80
     1.2     1.2
       0      80
Pier Skew, UpSta & Num, DnSta & Num=  ,3865.73, 2 ,3892.02, 2 , 0 , 0 , 0 ,,
     1.2     1.2
       0      80
     1.2     1.2
       0      80
BR Coef=-1 , 1 , 1 ,1.25, 0 ,,,.8,-1,2,0,
WSPro=,,,, 1 ,,,, 0 ,,,, 0 ,,,,-1 ,-1 ,-1 , 0 , 0 , 0 , 0 , 0
BC Design=,, 0 ,, 0 ,,,,,,

Type RM Length L Ch R = 1 ,30412   ,37.89,35.65,47.33
BEGIN DESCRIPTION:
Copied cross-section 30376/XS3
END DESCRIPTION:
XS GIS Cut Line= 6
     3046926.787    13809788.469     3046928.055    13809775.491
     3045263.962    13806386.585      3045175.69    13806280.497
     3044355.615    13802999.045     3044311.491    13802731.386
#Sta/Elev= 30
       0   82.37  215.37   80.46  450.85   82.87    1136   83.16 1364.54   81.02
 1704.17   83.91 2138.65   80.98 2589.84   83.38 2736.81   80.65 2872.94   82.72
 3057.75   80.51 3274.99   81.83 3341.83   79.65 3451.47   81.99 3625.91   79.69
 3827.38   80.97 3864.17   67.34 3890.68   68.37  3894.4   72.26 3931.32    81.1
 5259.25   82.38 5305.63   80.52 5630.32   84.95 5905.04      83 6372.46   84.79
 6681.69   81.04 6723.65   83.22 7006.38   81.43 7176.45   84.71 7580.13   85.29
#Mann= 3 , 0 , 0
       0     .15       0 3827.38     .04       0 3931.32     .15       0
#XS Ineff= 2 , 0
       0    3612            3974       0
Permanent Ineff=
       T       T
Bank Sta=3827.38,3931.32
XS Rating Curve= 0
Exp/Cntr=.5,.3

Type RM Length L Ch R = 1 ,30376   ,71.51,50.79,62.71
BEGIN DESCRIPTION:
Surveyed Cross-Section/XS4
END DESCRIPTION:
XS GIS Cut Line= 6
     3046950.135    13809781.733     3046950.785    13809774.767
     3045291.964    13806364.495     3045203.692    13806258.407
     3044390.295    13802966.822     3044332.337    13802711.429
#Sta/Elev= 30
       0   82.32 1191.87   83.16 1360.63   81.04 1677.56   83.91 2144.61   80.51
 2261.37   82.77 2592.25   83.35 2761.78   80.38 2928.59   82.83 3045.35   80.38
 3245.51   82.11 3352.28   79.46 3445.68   81.68 3833.38   80.97 3870.17   67.34
 3896.68   68.37  3900.4   72.26 3937.32    81.1  5169.2   82.35 5308.26    80.5
 5370.06   82.87 5509.12   81.89 5632.73   85.43  5895.4   83.03 6297.14   83.11
 6358.94   85.28 6667.96   81.24  6844.3   84.34 6961.54   81.28  7589.8   84.81
#Mann= 3 , 0 , 0
       0     .15       0 3833.38     .04       0 3937.32     .15       0
#XS Ineff= 2 , 0
       0    3623            3987       0
Permanent Ineff=
       T       T
Bank Sta=3833.38,3937.32
XS Rating Curve= 0
Exp/Cntr=.3,.1

Type RM Length L Ch R = 1 ,30325   ,478.58,173.74,251.55
BEGIN DESCRIPTION:
Copied cross-section 30376
END DESCRIPTION:
XS GIS Cut Line= 6
     3047013.881    13809763.341     3047016.168    13809744.789
     3045333.062    13806334.485      3045244.79    13806228.397
      3044433.21    13802980.795     3044354.565    13802676.499
#Sta/Elev= 30
       0   82.51  1371.4   81.51 1744.11   83.86 2179.08   80.68 2286.51   82.53
 2480.17    80.8 2613.99   83.32 2781.26   80.22 2948.53   82.71 3082.35   80.33
 3316.54   81.82 3366.72   79.36 3863.38   80.97 3900.17   67.34 3926.68   68.37
  3930.4   72.26 3967.32    81.1 5254.25   82.22 5331.55   80.32 5377.94   82.71
 5501.63   81.53 5640.78   84.84 5826.31   82.87 6367.46   84.83 6661.23   81.35
  6831.3    84.2 6954.99   81.06 7029.05    83.6 7255.79   81.79  7589.8   84.81
#Mann= 3 , 0 , 0
       0     .15       0 3863.38     .04       0 3967.32     .15       0
#XS Ineff= 2 , 0
       0    3648            4015       0
Permanent Ineff=
       T       T
Bank Sta=3863.38,3967.32
XS Rating Curve= 0
Exp/Cntr=.3,.1

Type RM Length L Ch R = 1 ,30151   ,954.25,944.91,547.9
BEGIN DESCRIPTION:
Surveyed Cross-Section
END DESCRIPTION:
XS GIS Cut Line= 6
     3047442.564    13809639.659     3047446.997    13809599.192
     3046707.135     13807107.46     3045490.051    13806203.059
     3045342.005    13806115.366     3044677.141    13802173.711
#Sta/Elev= 30
       0   82.27  481.66   81.52  626.64   85.59  904.51   85.78 1315.12   81.36
  1861.5   80.99 2017.29   83.21 2234.67   81.18 2328.87   83.32 2603.55   79.91
 2748.87   83.17 3251.86   83.81 3402.75   80.86 3916.52   82.14 4006.33   78.73
 4190.96   81.19 4228.88   68.01  4241.2   67.42 4296.72   81.75 5607.24   80.53
 5730.75   82.85 6412.37   83.79 6886.86   81.28 7107.71   84.53  7191.1   82.04
 7480.12   84.34  7708.3   81.71 7906.05   84.23 8012.54   81.26 8325.69   84.43
#Mann= 3 , 0 , 0
       0     .15       0 4190.96     .04       0 4296.72      .1       0
#XS Ineff= 2 , 0
       0    3976            4387       0
Permanent Ineff=
       T       T
Bank Sta=4190.96,4296.72
XS Rating Curve= 0
Exp/Cntr=.3,.1