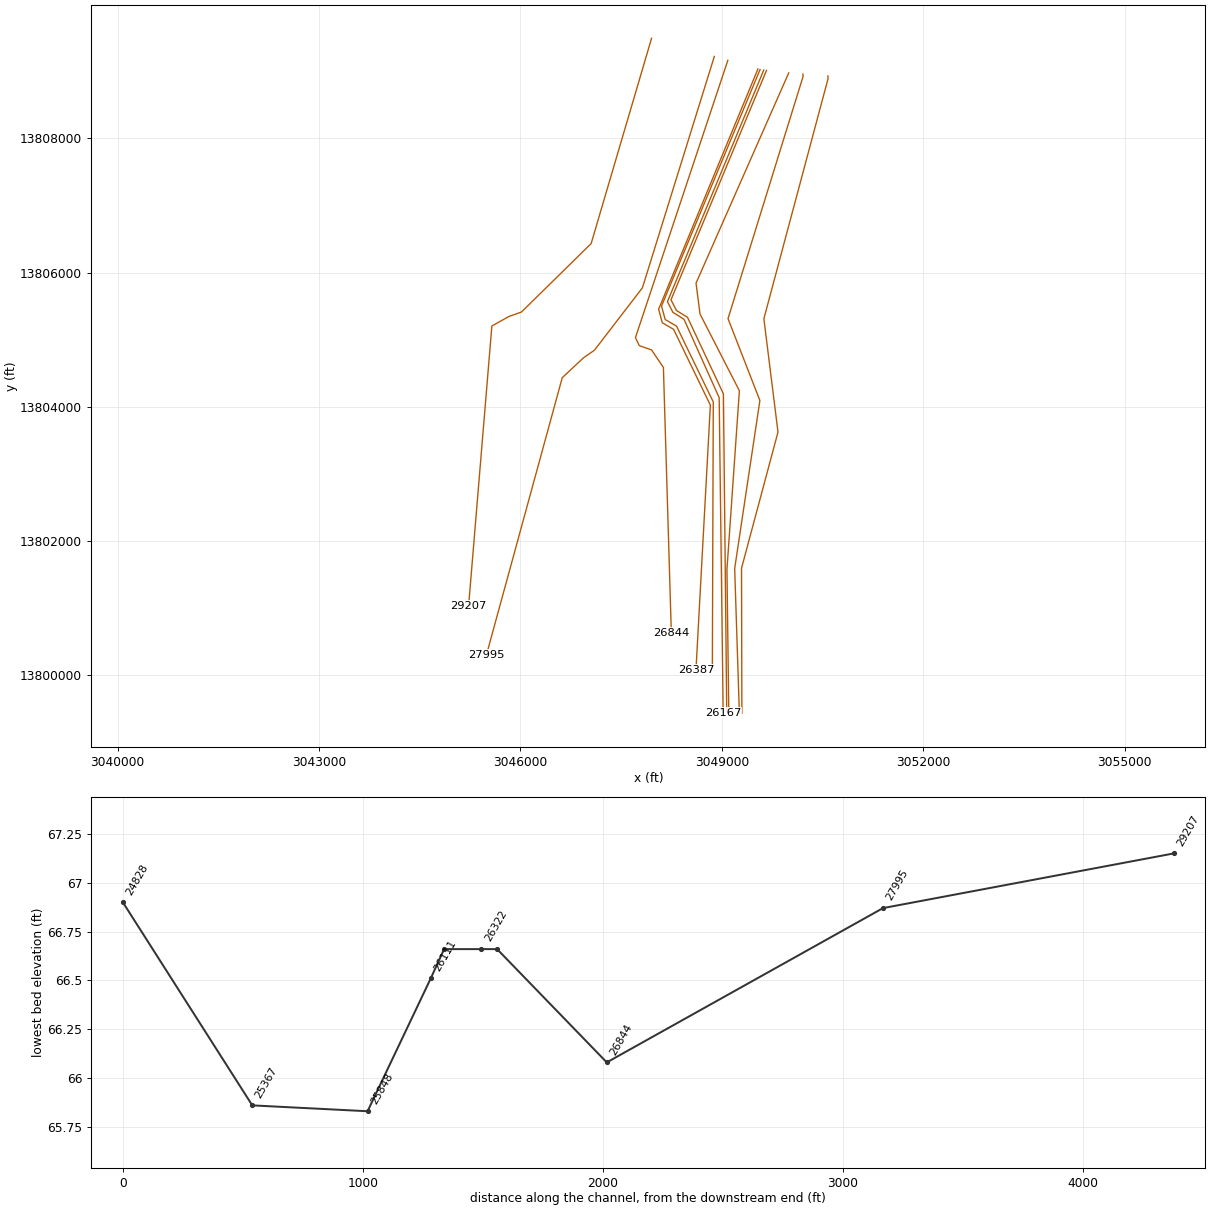
HEC-RAS study D118-00-00.prj: D118-00-00

--- D118-00-00.g03 (geometry) --- (continued)

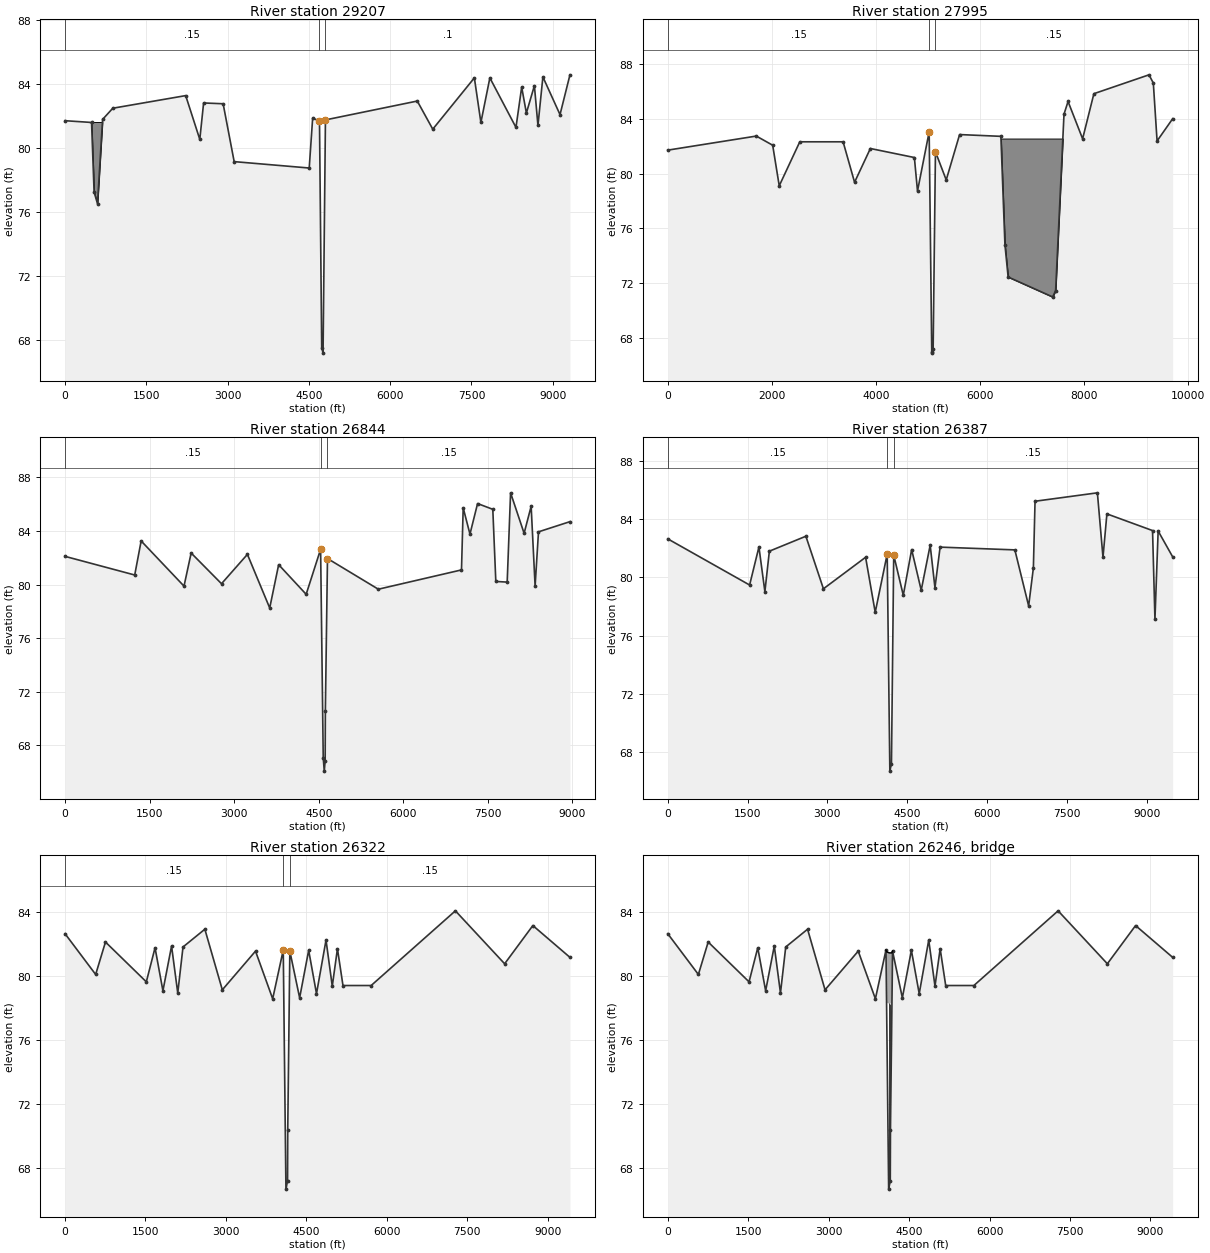
Type RM Length L Ch R = 1 ,29207   ,1487.55,1211.75,1200.27
BEGIN DESCRIPTION:
Surveyed Cross-Section
END DESCRIPTION:
XS GIS Cut Line= 6
     3047953.725    13809492.182     3047054.255    13806434.048
     3046016.134    13805413.672     3045826.344    13805345.919
     3045575.526    13805205.246     3045229.383    13801039.774
#Sta/Elev= 30
       0   81.69  489.36   81.58  536.35   77.22  599.01    76.5  692.99   81.77
  880.95   82.47 2226.28   83.26 2486.68   80.52 2556.98    82.8 2917.24   82.75
 3120.87   79.13 4505.85   78.73 4568.95   81.84 4695.11   81.69 4736.24    67.5
  4761.1   67.15 4805.16   81.74 6499.51   82.92 6785.49   81.16 7553.12   84.37
 7673.54   81.58  7839.1   84.37 8320.76   81.27 8426.12   83.79 8512.96   82.17
  8660.7   83.88 8726.36   81.39 8817.46   84.43 9133.55   82.07 9316.91   84.56
#Mann= 3 , 0 , 0
       0     .15       0 4695.11     .04       0 4805.16      .1       0
#XS Ineff= 2 , 0
       0    4477            5021       0
Permanent Ineff=
       T       T
#Block Obstruct= 1 ,-1
  451.61  696.77   81.61
Bank Sta=4695.11,4805.16
XS Rating Curve= 0
Exp/Cntr=.3,.1

Type RM Length L Ch R = 1 ,27995   ,162.47,1150.7,1578.01
BEGIN DESCRIPTION:
Surveyed Cross-Section
END DESCRIPTION:
XS GIS Cut Line= 6
     3048888.729    13809222.419     3047817.918    13805774.521
     3047102.852    13804844.241     3046939.644    13804730.925
     3046623.827     13804434.64     3045494.459    13800303.451
#Sta/Elev= 30
       0   81.72 1701.52   82.75 2016.16   82.08 2142.02   79.11 2537.03   82.33
 3369.13   82.33 3589.39   79.37 3893.12   81.84 4738.58   81.18 4798.65   78.73
  5022.6   83.06 5072.65   66.92 5086.73   66.87 5099.19   67.18 5143.65    81.6
 5350.43   79.54 5607.53   82.86  6400.6   82.73 6478.35   74.81 6539.84   72.44
 7395.67   70.98 7452.56   71.44 7613.53   84.35 7691.28   85.28 7971.19   82.55
 8187.71   85.85 9246.33   87.23  9329.7   86.63 9401.83   82.39 9701.48   84.02
#Mann= 3 , 0 , 0
       0     .15       0  5022.6     .04       0 5143.65     .15       0
#XS Ineff= 2 , 0
       0    4779            5340       0
Permanent Ineff=
       T       T
#Block Obstruct= 1 ,-1
    6400  7612.9   82.57
Bank Sta=5022.6,5143.65
XS Rating Curve= 0
Exp/Cntr=.3,.1

Type RM Length L Ch R = 1 ,26844   ,261.76,456.92,412.1
BEGIN DESCRIPTION:
Surveyed Cross-Section
END DESCRIPTION:
XS GIS Cut Line= 6
     3049090.106    13809164.318     3047713.782    13805031.686
     3047771.253    13804912.481       3047953.4    13804849.033
     3048130.325    13804587.373     3048248.306    13800634.796
#Sta/Elev= 30
       0    82.1 1235.87   80.71 1349.87   83.25 2110.01   79.88  2236.7   82.35
 2775.14   80.06 3234.39   82.25 3630.05   78.25 3788.66   81.48 4276.48   79.27
 4532.67   82.63 4579.35   67.08 4597.64   66.08 4613.42   66.86 4617.12   70.59
 4654.68   81.94 5556.42   79.65 7031.48   81.09  7061.5   85.72 7181.55   83.76
 7316.61   86.04 7586.73   85.61 7640.18   80.23 7841.84   80.18 7901.87   86.84
 8141.98   83.82 8266.76   85.84 8337.07   79.88 8397.09   83.93 8955.05   84.69
#Mann= 3 , 0 , 0
       0     .15       0 4532.67     .04       0 4654.68     .15       0
#XS Ineff= 2 , 0
       0    4231            4844       0
Permanent Ineff=
       T       T
Bank Sta=4532.67,4654.68
XS Rating Curve= 0
Exp/Cntr=.3,.1

Type RM Length L Ch R = 1 ,26387   ,23.51,65.02,61.54
BEGIN DESCRIPTION:
Copied cross-section 26322/XS1
END DESCRIPTION:
XS GIS Cut Line= 6
     3049537.924    13809035.116     3048059.266    13805455.252
     3048113.656     13805253.37     3048282.201    13805155.547
     3048829.871    13804025.122     3048615.416    13800079.835
#Sta/Elev= 30
       0   82.66 1538.49   79.48  1713.4    82.1 1825.45   79.02 1909.48   81.81
 2595.73   82.84 2925.44   79.22 3718.04   81.39 3898.91    77.6 4123.78   81.61
 4173.83   66.66 4203.99   67.18 4246.57   81.54 4426.39   78.77 4583.58   81.92
 4763.23   79.12 4931.65   82.22 5021.47   79.29 5118.44   82.09 6522.94    81.9
 6782.22   78.04 6871.13   80.65  6902.4   85.25 8074.13   85.83 8179.29   81.39
 8252.93   84.38 9110.66   83.23 9155.73   77.11 9215.82    83.2 9488.88   81.42
#Mann= 3 , 0 , 0
       0     .15       0 4123.78     .04       0 4246.57     .15       0
#XS Ineff= 2 , 0
       0    3958            4433       0
Permanent Ineff=
       T       T
Bank Sta=4123.78,4246.57
XS Rating Curve= 0
Exp/Cntr=.5,.3

Type RM Length L Ch R = 1 ,26322   ,55.46,155.58,139.86
BEGIN DESCRIPTION:
Surveyed Cross-Section/XS2
END DESCRIPTION:
XS GIS Cut Line= 6
     3049570.048    13809027.454     3048102.555     13805503.32
     3048156.945    13805301.438      3048325.49    13805203.616
      3048873.16     13804073.19     3048859.499    13800140.828
#Sta/Elev= 30
       0   82.63  571.12   80.08  753.74   82.11 1515.69   79.62  1678.1   81.75
 1825.13   79.06 1986.22   81.86 2101.77   78.92  2199.7    81.8 2606.85   82.91
 2932.56   79.12 3551.43   81.54 3871.54   78.56 4068.78   81.61 4118.83   66.66
 4148.99   67.18 4152.47   70.34 4191.57   81.54 4374.23   78.62 4542.65   81.59
 4688.61   78.88 4866.09   82.23 4982.77   79.35 5079.15   81.69 5182.36   79.39
 5707.72   79.39 7278.31   84.06 8196.51   80.75 8722.74   83.14 9414.42   81.15
#Mann= 3 , 0 , 0
       0     .15       0 4068.78     .04       0 4191.57     .15       0
#XS Ineff= 2 , 0
       0    3919            4383       0
Permanent Ineff=
       T       T
Bank Sta=4068.78,4191.57
XS Rating Curve= 0
Exp/Cntr=.5,.3

Type RM Length L Ch R = 3 ,26246   ,,,
BEGIN DESCRIPTION:
Dairy Ashford bridge
END DESCRIPTION:
Bridge Culvert--1,0,-1,-1, 0
Deck Dist Width WeirC Skew NumUp NumDn MinLoCord MaxHiCord MaxSubmerge Is_Ogee
30.29,95,2.6,0, 7, 7, , , .95, 0, 0,0,,
 4068.13 4084.33 4084.33 4130.33 4176.33 4176.33 4191.57
    81.6   81.49   81.49   81.43   81.43   81.43   81.54
       0       0    78.3   78.26   78.26       0       0
  3951.8    3968    3968    4014    4060    4060 4074.58
    81.6   81.49   81.49   81.43   81.43   81.43   81.54
       0       0    78.3    78.3   78.26       0       0
Pier Skew, UpSta & Num, DnSta & Num=  ,4118.72, 2 ,4000.1, 2 , 0 , 0 , 0 ,,
     1.2     1.2
       0      80
     1.2     1.2
       0      80
Pier Skew, UpSta & Num, DnSta & Num=  ,4148.72, 2 ,4030.1, 2 , 0 , 0 , 0 ,,
     1.2     1.2
       0      80
     1.2     1.2
       0      80
BR Coef=-1 , 1 , 1 ,1.25, 0 ,,,.8,-1,2,0,
WSPro=,,,, 1 ,,,, 0 ,,,, 0 ,,,,-1 ,-1 ,-1 , 0 , 0 , 0 , 0 , 0
BC Design=,, 0 ,, 0 ,,,,,,

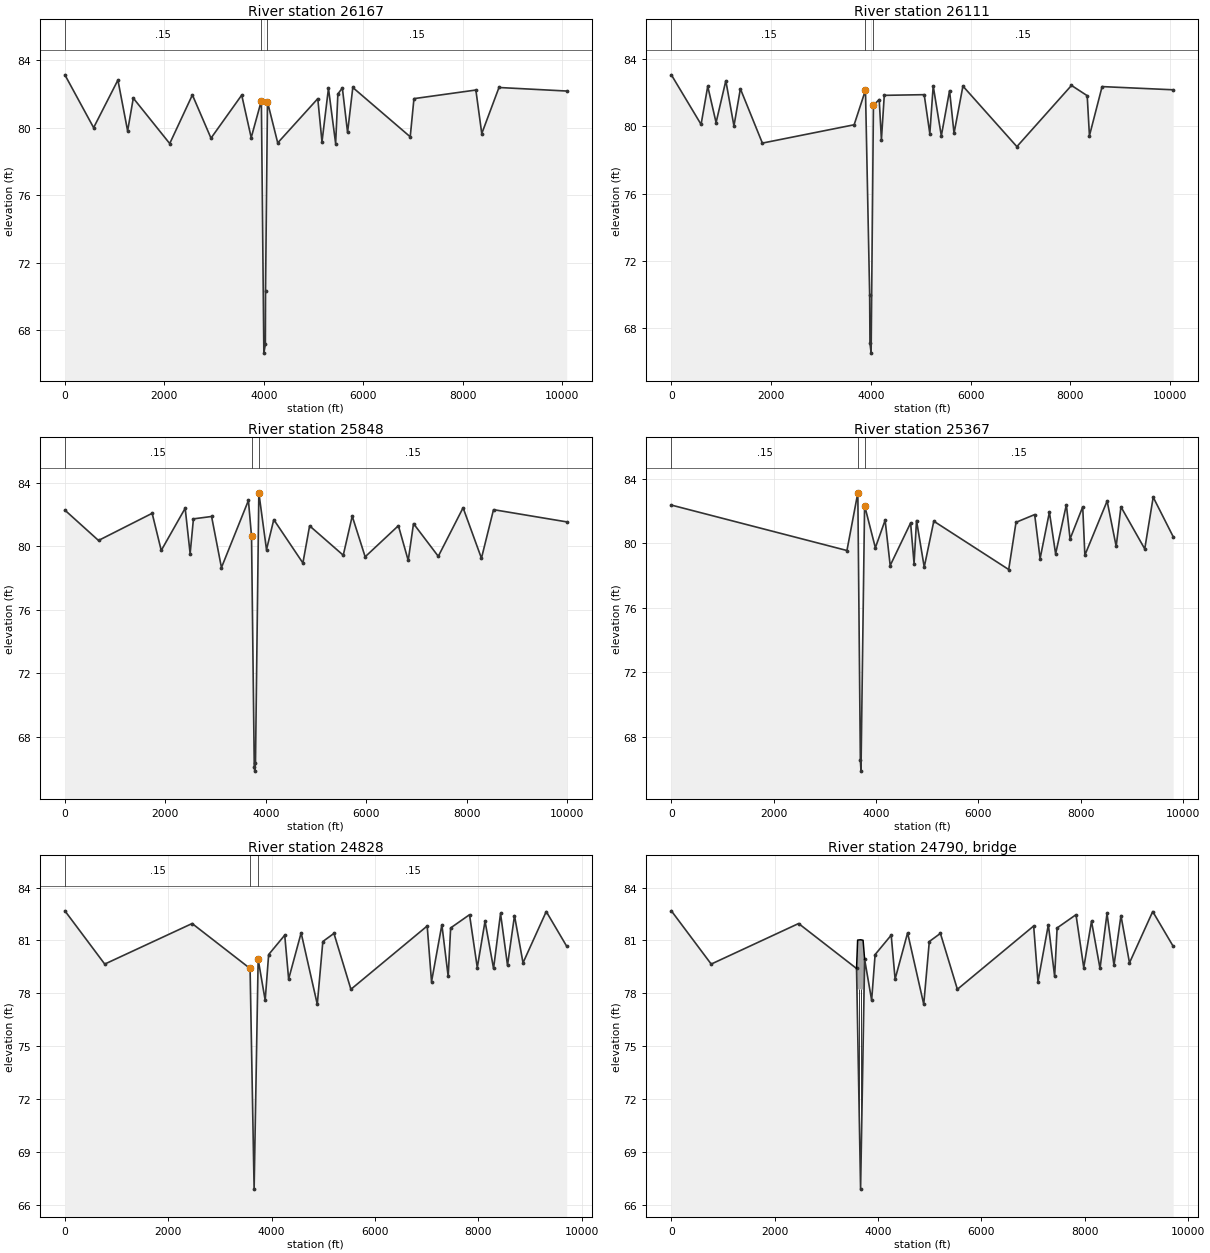
Type RM Length L Ch R = 1 ,26167   ,38.27,55.83,66.53
BEGIN DESCRIPTION:
Surveyed Cross-Section/XS3
END DESCRIPTION:
XS GIS Cut Line= 6
     3049624.591    13809018.936     3048190.414     13805567.88
     3048272.086    13805408.623     3048436.772    13805306.077
      3048961.02     13804137.75     3049020.424    13799440.631
#Sta/Elev= 30
       0   83.14  578.07   80.01 1066.53   82.83 1261.92   79.82 1375.89   81.76
 2108.59   79.07 2564.49   81.95 2938.63   79.39 3556.48   81.94 3747.36   79.42
  3951.8   81.61 4001.85   66.66 4032.01   67.18 4035.49   70.34 4074.59   81.54
 4280.71   79.11 5086.46   81.73 5170.93   79.17 5301.26   82.34 5445.61   79.07
 5490.61   82.01 5580.62   82.36 5685.63   79.73 5790.64   82.39 6945.73   79.47
 7020.73   81.73 8265.83   82.24 8384.52   79.66 8730.86   82.3910092.84   82.18
#Mann= 3 , 0 , 0
       0     .15       0  3951.8     .04       0 4074.59     .15       0
#XS Ineff= 2 , 0
       0    3840            4291       0
Permanent Ineff=
       T       T
Bank Sta=3951.8,4074.59
XS Rating Curve= 0
Exp/Cntr=.5,.3

Type RM Length L Ch R = 1 ,26111   ,255,263.11,207.16
BEGIN DESCRIPTION:
Copied cross-section 26167/XS4
END DESCRIPTION:
XS GIS Cut Line= 6
     3049665.157    13809012.601     3048243.289    13805595.697
     3048324.961     13805436.44     3048489.646    13805333.893
     3049024.273     13804193.39     3049073.298    13799468.447
#Sta/Elev= 30
       0   83.06  596.34   80.11  729.68   82.38  897.03   80.22 1092.46   82.71
 1255.33   80.02 1384.33   82.23 1825.35      79 3665.71   80.09 3892.98   82.15
 3976.78   69.97 3982.91   67.11 4006.21   66.51 4052.59   81.25 4168.31   81.59
 4212.72    79.2 4269.83   81.84 5070.64   81.88 5183.44   79.56 5251.11    82.4
 5414.14   79.43 5579.15   82.12 5668.95   79.58 5847.11   82.39 6929.22   78.79
 8024.28   82.43  8339.3   81.82  8384.3   79.44  8638.3   82.3610063.44   82.17
#Mann= 3 , 0 , 0
       0     .15       0 3892.98     .04       0 4052.59     .15       0
#XS Ineff= 2 , 0
       0    3798            4250       0
Permanent Ineff=
       T       T
Bank Sta=3892.98,4052.59
XS Rating Curve= 0
Exp/Cntr=.3,.1

Type RM Length L Ch R = 1 ,25848   ,625.23,480.26,372.34
BEGIN DESCRIPTION:
Surveyed Cross-Section
END DESCRIPTION:
XS GIS Cut Line= 6
     3049996.762    13808976.827     3048616.292    13805843.945
     3048676.041      13805383.2     3049261.935    13804240.253
     3049076.923    13801578.039       3049104.2     13799435.78
#Sta/Elev= 30
       0   82.27   669.2   80.36 1737.06   82.07 1917.77   79.73  2394.2   82.39
 2492.95   79.53 2558.48   81.72 2919.91   81.87 3116.15   78.65 3653.16   82.88
 3715.03   80.61 3769.56   66.06 3780.12   65.83 3793.48   66.36 3860.37   83.36
 4012.88   79.78 4157.75   81.67 4737.22   78.94 4870.94   81.28 5540.41   79.43
    5719   81.89 5976.46   79.33 6638.05   81.29 6833.52    79.1 6938.77   81.42
 7431.87   79.36 7925.52   82.42 8290.99   79.24 8531.01    82.3 9987.85   81.53
#Mann= 3 , 0 , 0
       0     .15       0 3715.03     .04       0 3860.37     .15       0
#XS Ineff= 2 , 0
       0    3620            4047       0
Permanent Ineff=
       T       T
Bank Sta=3715.03,3860.37
XS Rating Curve= 0
Exp/Cntr=.3,.1

Type RM Length L Ch R = 1 ,25367   ,510.16,539.3,487.62
BEGIN DESCRIPTION:
Surveyed Cross-Section/XS1
END DESCRIPTION:
XS GIS Cut Line= 6
      3050208.35    13808959.771     3050210.218    13808922.239
     3049092.712     13805314.97       3049567.4    13804094.463
     3049191.918    13801590.744     3049261.661    13799437.092
#Sta/Elev= 30
       0   82.37 3432.68   79.55 3645.54   83.13 3694.86   66.56 3707.22   65.86
  3777.7   82.34  3988.4   79.72  4178.9   81.43  4278.1   78.62 4677.17   81.26
 4744.84   78.74 4792.86   81.41 4943.69   78.52 5130.68   81.37 6595.23   78.37
 6737.98    81.3 7102.49   81.78 7208.66   79.05 7390.68   81.93 7512.02   79.34
 7722.06   82.39 7794.75   80.27 8041.88   82.26 8083.83   79.26 8519.06   82.62
 8696.05   79.81  8789.2   82.26 9254.44   79.65 9419.53   82.86 9810.14   80.41
#Mann= 3 , 0 , 0
       0     .15       0 3645.54     .04       0  3777.7     .15       0
#XS Ineff= 2 , 0
       0    3550            3969       0
Permanent Ineff=
       T       T
Bank Sta=3645.54,3777.7
XS Rating Curve= 0
Exp/Cntr=.5,.3

Type RM Length L Ch R = 1 ,24828   ,94.11,89.96,95.52
BEGIN DESCRIPTION:
Surveyed Cross-Section/XS2
END DESCRIPTION:
XS GIS Cut Line= 6
     3050580.144    13808931.599     3050582.924    13808891.585
     3049626.725    13805313.243      3049837.02    13803624.498
     3049293.991    13801596.005     3049298.972    13799432.301
#Sta/Elev= 30
       0   82.68  771.05   79.66  2462.2   81.96 3583.27   79.41 3661.45    66.9
 3739.63   79.93 3875.37   77.61 3942.58    80.2 4253.71    81.3 4329.29   78.81
 4571.15   81.43 4883.51   77.38 4991.05   80.94 5206.02    81.4 5534.18   78.23
 7010.15   81.82 7093.91   78.66 7294.17   81.89 7416.19   78.96  7463.8   81.71
 7829.28   82.46 7979.28   79.46 8129.28   82.09 8294.28   79.41 8429.28   82.53
 8564.28   79.59 8699.28   82.41 8864.28   79.73 9313.72   82.64 9709.48   80.67
#Mann= 3 , 0 , 0
       0     .15       0 3583.27     .04       0 3739.63     .15       0
#XS Ineff= 2 , 0
       0    3397            3933       0
Permanent Ineff=
       T       T
Bank Sta=3583.27,3739.63
XS Rating Curve= 0
Exp/Cntr=.5,.3

Type RM Length L Ch R = 3 ,24790   ,,,
BEGIN DESCRIPTION:
Keegans  bridge
END DESCRIPTION:
Bridge Culvert--1,0,-1,-1, 0
Deck Dist Width WeirC Skew NumUp NumDn MinLoCord MaxHiCord MaxSubmerge Is_Ogee
28.98,32,2.6,0, 7, 7, , , .95, 0, 0,0,,
 3583.27 3604.26 3604.26 3661.45  3709.6  3709.6 3739.63
   79.41   81.02   81.02   81.04   81.01   81.01   79.93
     -.3       0   78.22   78.24   78.21       0     -.3
 3594.27 3615.27 3615.27 3672.45 3720.61 3720.61 3750.63
   79.41   81.02   81.02   81.04   81.01   81.01   79.93
     -.3       0   78.22   78.24   78.21       0     -.3
Pier Skew, UpSta & Num, DnSta & Num=  ,3639.37, 2 ,3650.38, 2 , 0 , 0 , 0 ,,
     1.2     1.2
       0      80
     1.2     1.2
       0      80
Pier Skew, UpSta & Num, DnSta & Num=  ,3674.49, 2 ,3685.5, 2 , 0 , 0 , 0 ,,
     1.2     1.2
       0      80
     1.2     1.2
       0      80
BR Coef=-1 , 1 , 1 ,1.25, 0 ,,,.8,-1,2,0,
WSPro=,,,, 1 ,,,, 0 ,,,, 0 ,,,,-1 ,-1 ,-1 , 0 , 0 , 0 , 0 , 0
BC Design=,, 0 ,, 0 ,,,,,,