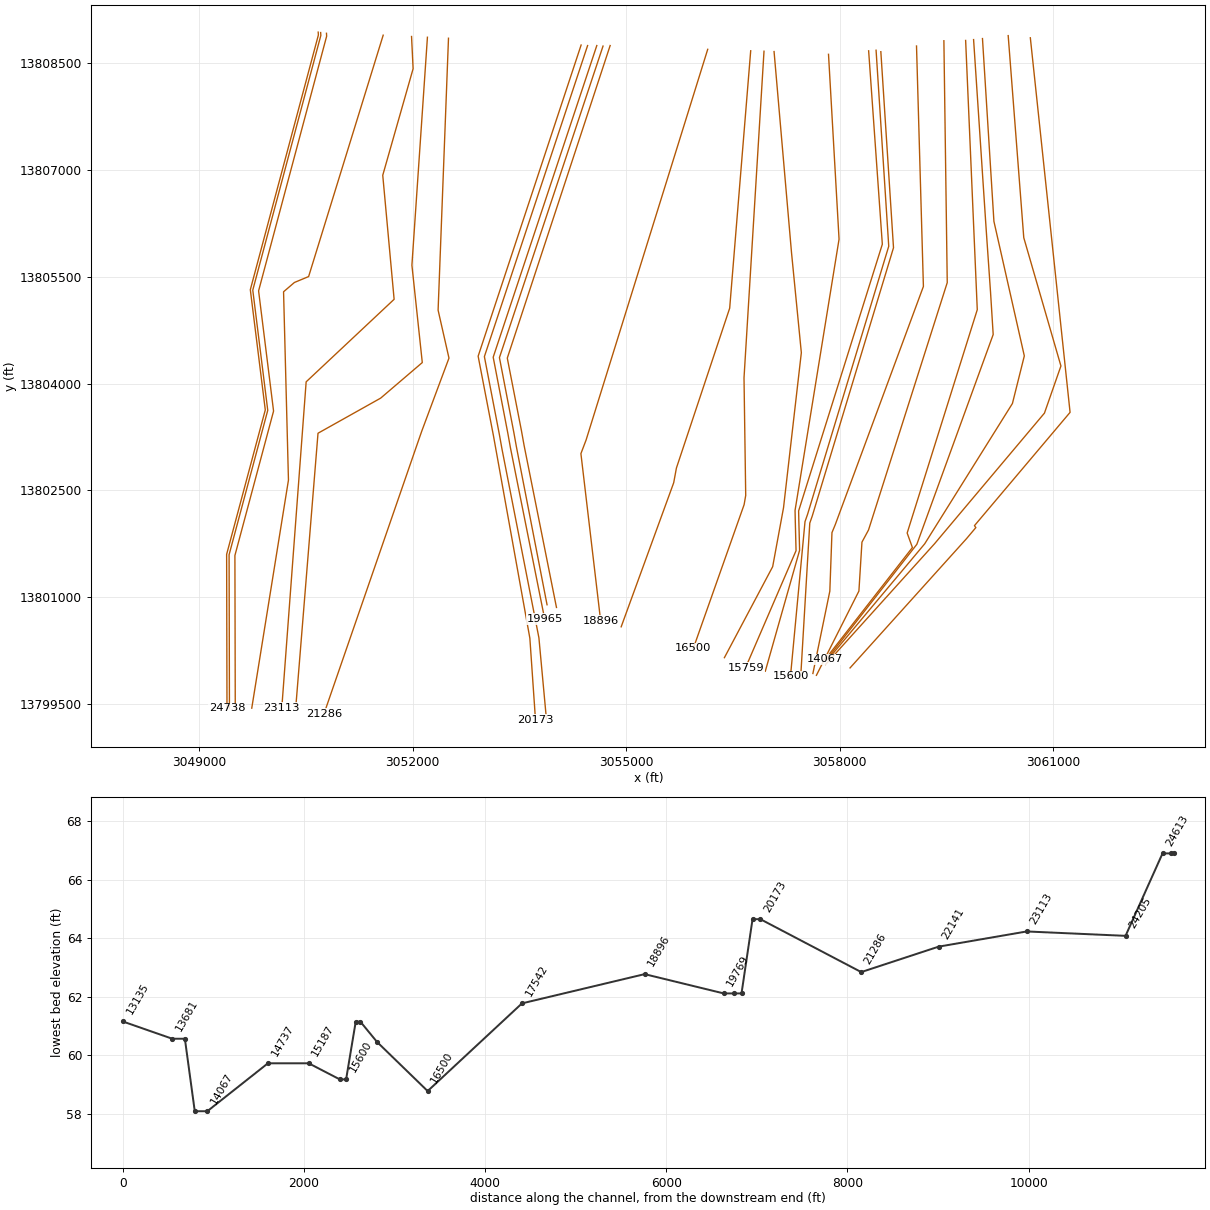
HEC-RAS study D118-00-00.prj: D118-00-00

--- D118-00-00.g03 (geometry) --- (continued)

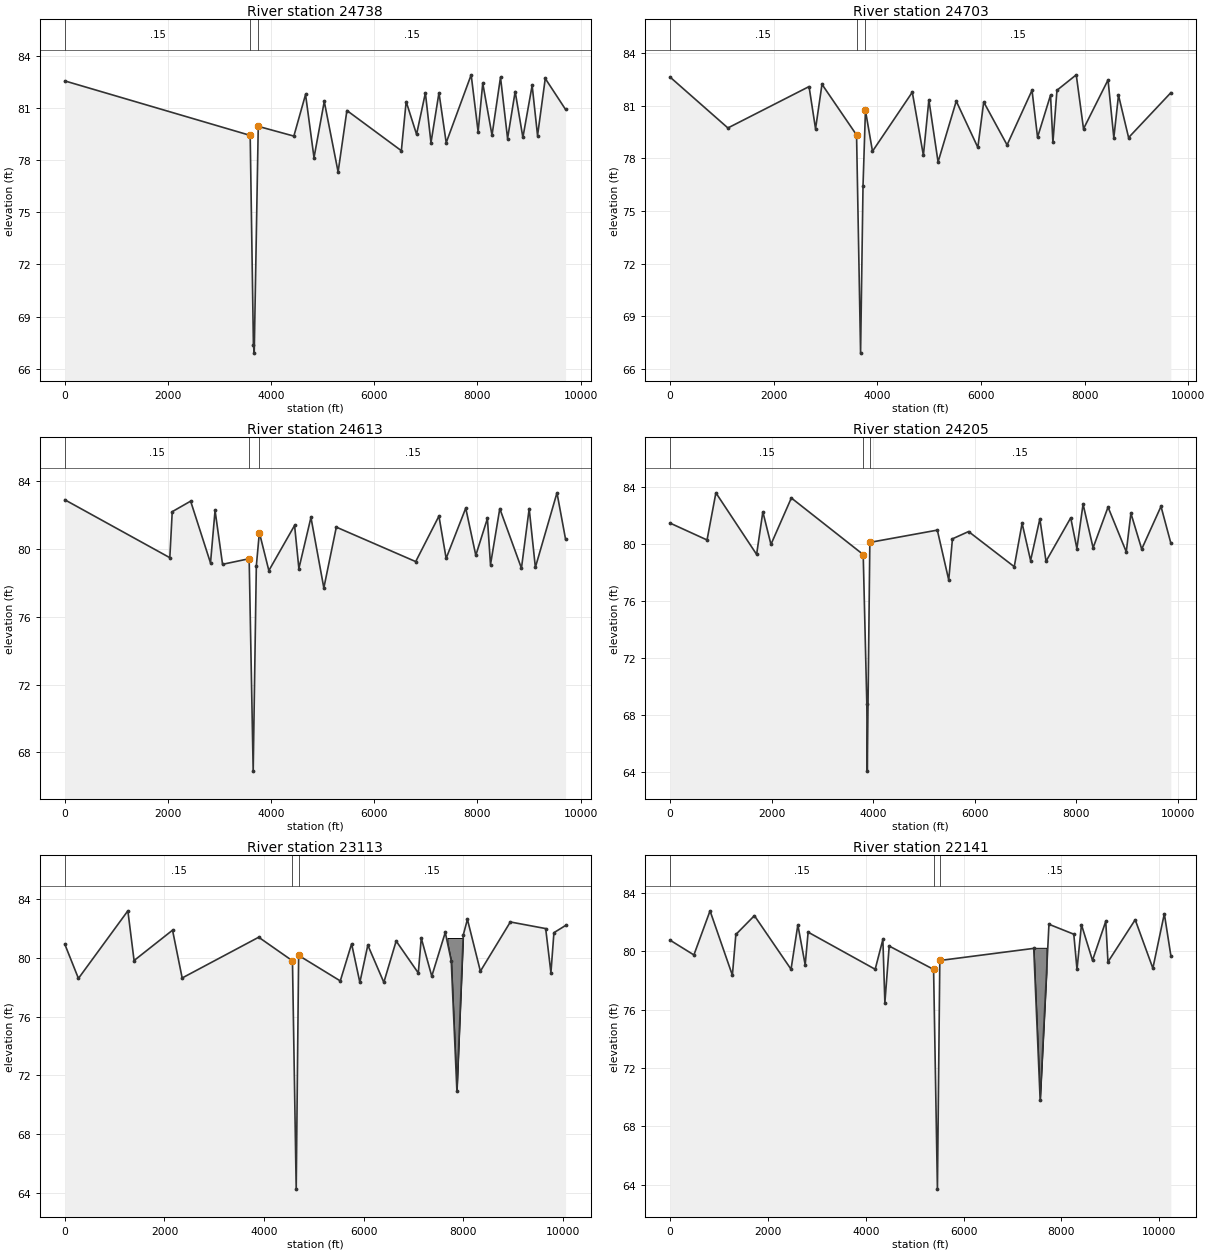
Type RM Length L Ch R = 1 ,24738   ,36.86,34.83,34.36
BEGIN DESCRIPTION:
Copied cross-section 24828/XS3
END DESCRIPTION:
XS GIS Cut Line= 6
     3050673.753    13808937.481     3050676.533    13808897.467
     3049720.335    13805319.125      3049930.63     13803630.38
     3049387.601    13801601.887     3049392.582    13799438.182
#Sta/Elev= 30
       0   82.54 3594.27   79.41 3656.81   67.39 3672.45    66.9 3750.63   79.93
 4441.04   79.37 4667.77   81.76 4831.78   78.13 5030.55   81.36 5299.14   77.31
 5469.54   80.84 6525.46   78.53 6618.63   81.35  6820.5   79.47 6991.31   81.85
    7100   78.99 7254.97   81.86 7395.04   78.99  7879.3   82.89 8013.99   79.62
 8103.78   82.41 8283.37   79.42 8447.99   82.75 8585.17   79.23 8732.34   81.93
 8881.99   79.29 9061.58   82.28 9166.34    79.4 9315.99   82.68 9709.49    80.9
#Mann= 3 , 0 , 0
       0     .15       0 3594.27     .04       0 3750.63     .15       0
#XS Ineff= 2 , 0
       0    3393            3955       0
Permanent Ineff=
       T       T
Bank Sta=3594.27,3750.63
XS Rating Curve= 0
Exp/Cntr=.5,.3

Type RM Length L Ch R = 1 ,24703   ,86.38,90.43,81.67
BEGIN DESCRIPTION:
Copied cross-section 24828/XS4
END DESCRIPTION:
XS GIS Cut Line= 6
     3050708.293    13808931.799     3050711.073    13808891.785
     3049754.874    13805313.443     3049965.169    13803624.698
      3049422.14    13801596.205     3049427.121    13799432.501
#Sta/Elev= 30
       0   82.64 1115.48   79.74 2681.82    82.1 2807.24   79.69 2931.41   82.23
 3598.84   79.34 3676.45    66.9 3723.36   76.44 3770.21   80.74 3906.25   78.41
 4674.76   81.78 4888.78   78.18 4994.59   81.34 5172.11    77.8 5522.94   81.27
 5939.56   78.63 6053.05   81.22 6504.04   78.77 6985.42   81.89 7092.08   79.21
 7342.57   81.61 7388.95   78.92 7466.79   81.89 7839.17   82.77 7979.48   79.69
 8452.75   82.48 8564.48   79.18 8654.48   81.61 8849.48   79.19 9664.97   81.75
#Mann= 3 , 0 , 0
       0     .15       0 3598.84     .04       0 3770.21     .15       0
#XS Ineff= 2 , 0
       0    3384            3959       0
Permanent Ineff=
       T       T
Bank Sta=3598.84,3770.21
XS Rating Curve= 0
Exp/Cntr=.3,.1

Type RM Length L Ch R = 1 ,24613   ,645.23,408.3,382.3
BEGIN DESCRIPTION:
Copied cross-section 24828
END DESCRIPTION:
XS GIS Cut Line= 6
     3050790.011    13808921.409     3050792.791    13808881.395
     3049836.592    13805303.053     3050046.887    13803614.308
     3049503.858    13801585.815     3049508.839    13799422.111
#Sta/Elev= 30
       0   82.88 2035.97   79.47 2082.54   82.18 2439.51    82.8 2824.77   79.16
 2913.09   82.25 3058.35   79.08 3574.27   79.41 3652.45    66.9 3713.37   78.98
 3772.26   80.95 3956.25   78.71 4455.07   81.37 4538.45   78.83  4772.5   81.84
 5022.36   77.69 5264.32   81.27 6803.86   79.24 7254.18   81.92 7393.93   79.43
 7774.09   82.39 7969.09   79.61  8194.1   81.78  8254.1   79.06  8434.1   82.36
  8854.1   78.85  9004.1   82.36  9124.1    78.9 9543.15   83.29 9709.49   80.56
#Mann= 3 , 0 , 0
       0     .15       0 3574.27     .04       0 3772.26     .15       0
#XS Ineff= 2 , 0
       0    3369            4005       0
Permanent Ineff=
       T       T
Bank Sta=3574.27,3772.26
XS Rating Curve= 0
Exp/Cntr=.3,.1

Type RM Length L Ch R = 1 ,24205   ,1081.51,1091.26,887.52
BEGIN DESCRIPTION:
Surveyed Cross-Section
END DESCRIPTION:
XS GIS Cut Line= 6
     3051586.831    13808894.822     3050539.334    13805503.768
     3050339.983    13805420.993     3050187.251    13805290.137
      3050256.09    13802644.808      3049740.52    13799441.081
#Sta/Elev= 30
       0   81.44  727.25   80.26  901.54   83.56 1703.22   79.25 1826.09   82.23
 1985.79   79.95 2387.11    83.2 3802.13   79.24 3873.43   68.77 3882.35   64.08
 3932.79   80.09  5261.6   80.95 5486.19   77.46 5559.39   80.34 5876.79   80.85
 6776.13   78.39 6931.04   81.43 7098.16   78.82 7280.48   81.74 7402.02   78.77
  7888.2   81.81 8009.74   79.66 8131.28   82.77 8328.79   79.71 8623.02   82.56
 8982.09   79.43 9073.25   82.13 9285.95   79.62 9665.77   82.61 9859.65   80.04
#Mann= 3 , 0 , 0
       0     .15       0 3802.13     .04       0 3932.79     .15       0
#XS Ineff= 2 , 0
       0    3562            4511       0
Permanent Ineff=
       T       T
Bank Sta=3802.13,3932.79
XS Rating Curve= 0
Exp/Cntr=.3,.1

Type RM Length L Ch R = 1 ,23113   ,1000.04,972.63,806.68
BEGIN DESCRIPTION:
Surveyed Cross-Section
END DESCRIPTION:
XS GIS Cut Line= 6
     3051985.197    13808876.211     3052007.135    13808423.831
     3051580.693    13806926.958     3051740.367    13805184.418
     3050504.622    13804025.039     3050162.388    13799444.595
#Sta/Elev= 30
       0   80.93  273.11    78.6 1265.33   83.21 1390.11   79.82 2162.29   81.89
 2355.47   78.63 3891.91   81.41 4569.65    79.8 4644.89   64.23 4693.81   80.17
 5529.78   78.43 5757.25   80.96 5922.71   78.33  6082.5   80.87 6404.05   78.33
 6651.48   81.15 7095.98   78.97 7155.43   81.35 7366.35   78.75 7637.49   81.74
 7756.92   79.81 7870.71   70.94 7998.49   81.56 8082.05   82.63 8342.15   79.09
 8943.64   82.45  9653.1      82 9758.39   78.99 9818.56   81.7210052.11   82.21
#Mann= 3 , 0 , 0
       0     .15       0 4569.65     .04       0 4693.81     .15       0
#XS Ineff= 2 , 0
       0    4403            5171       0
Permanent Ineff=
       T       T
#Block Obstruct= 1 ,-1
    7680 8020.65   81.36
Bank Sta=4569.65,4693.81
XS Rating Curve= 0
Exp/Cntr=.3,.1

Type RM Length L Ch R = 1 ,22141   ,694.88,854.17,1159.15
BEGIN DESCRIPTION:
Surveyed Cross-Section
END DESCRIPTION:
XS GIS Cut Line= 6
     3052208.297    13808865.788     3051990.293    13805663.443
     3052136.084    13804295.793     3051551.369    13803796.169
      3050671.24    13803303.031     3050358.197    13799446.226
#Sta/Elev= 30
       0   80.75  486.44   79.74  816.23   82.76 1273.07   78.35  1343.9   81.14
 1723.16   82.43 2472.22   78.76  2611.3    81.8 2761.39   79.06 2821.43    81.3
 4192.21   78.76 4349.58    80.8 4390.48   76.46 4478.82   80.35 5386.27   78.75
 5464.65   63.71 5513.64   79.36 7433.55   80.19 7564.58   69.83 7744.74   81.84
 8252.48   81.16    8318   78.75  8409.2   81.81 8634.94   79.37 8905.83   82.04
 8950.97   79.26  9507.8   82.15 9868.98   78.8310103.28   82.5610236.46    79.7
#Mann= 3 , 0 , 0
       0     .15       0 5386.27     .04       0 5513.64     .15       0
#XS Ineff= 2 , 0
       0    5177            5742       0
Permanent Ineff=
       T       T
#Block Obstruct= 1 ,-1
 7416.77 7695.48   80.23
Bank Sta=5386.27,5513.64
XS Rating Curve= 0
Exp/Cntr=.3,.1

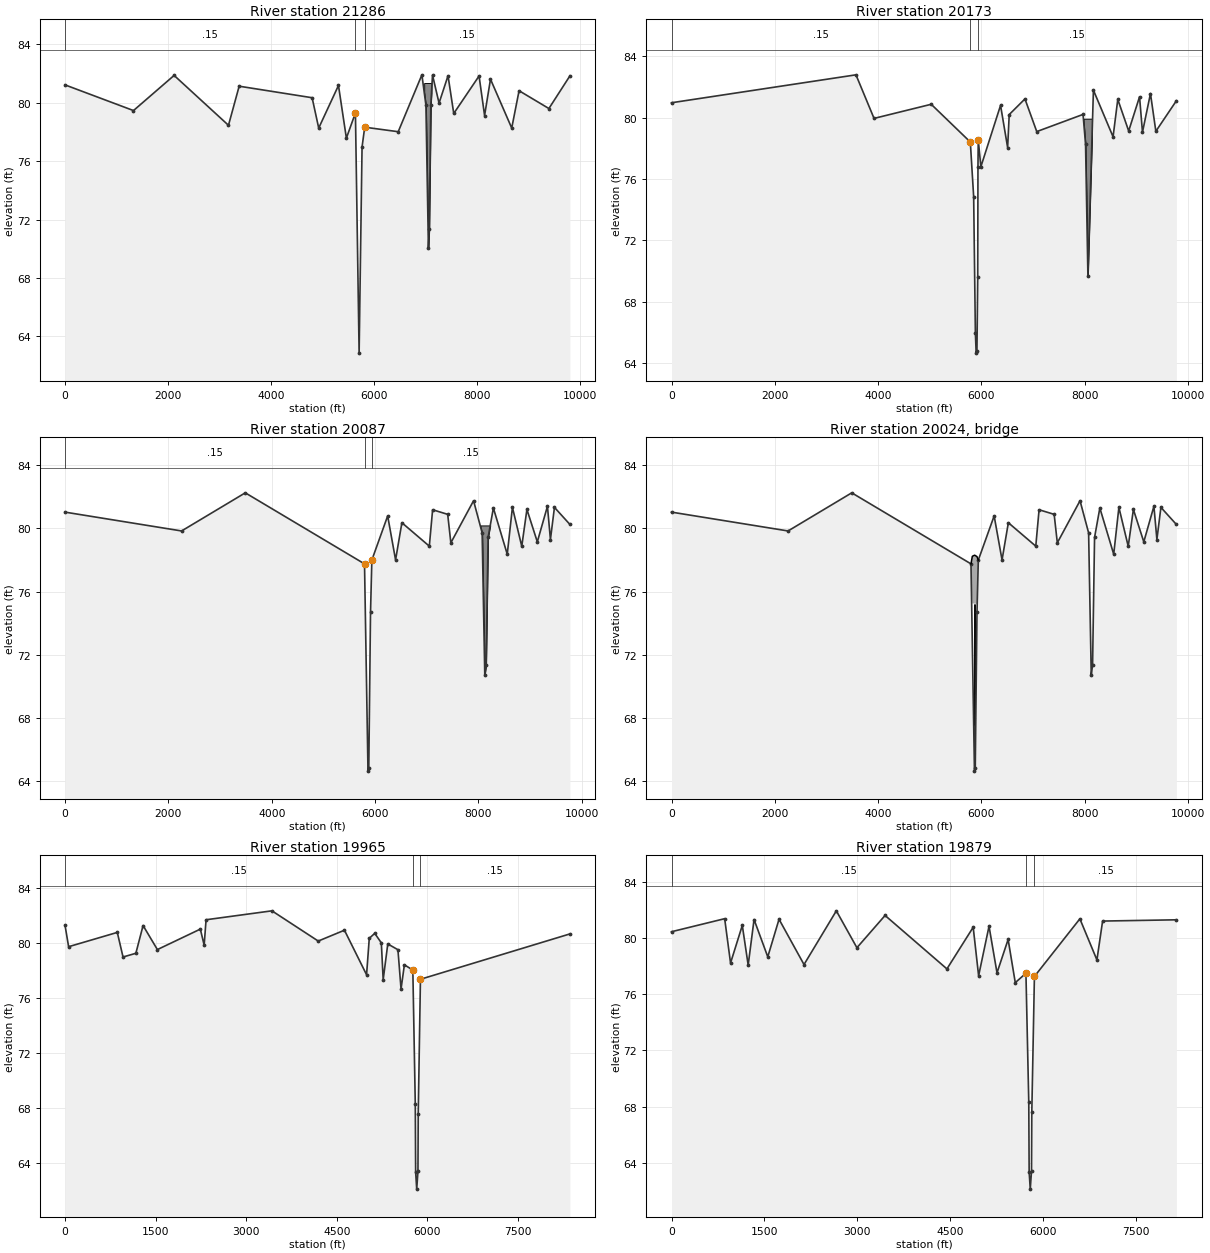
Type RM Length L Ch R = 1 ,21286   ,1032.96,1113.11,1241.03
BEGIN DESCRIPTION:
Surveyed Cross-Section
END DESCRIPTION:
XS GIS Cut Line= 6
     3052504.193    13808851.964      3052358.24    13805031.686
     3052510.973    13804358.274      3052127.82    13803330.172
     3052063.032    13803143.987     3050753.857    13799358.286
#Sta/Elev= 30
       0   81.23 1330.43   79.47 2120.26   81.88 3176.78   78.46 3384.45   81.14
 4802.55   80.35 4930.61   78.27  5314.8   81.19  5468.5   77.58  5644.3   79.31
 5716.08   62.84 5773.13   76.97 5824.82   78.33 6476.07   78.02 6936.35   81.92
 7014.44   79.84 7062.97   70.04  7079.2   71.33 7109.89   79.88 7142.68    81.9
 7269.65   79.98 7444.24   81.86 7555.34   79.27 8047.36   81.84 8154.75   79.13
 8269.57   81.62 8682.23   78.27 8825.07   80.83 9404.66   79.61 9813.57   81.85
#Mann= 3 , 0 , 0
       0     .15       0  5644.3     .04       0 5824.82     .15       0
#XS Ineff= 2 , 0
       0    5487            5992       0
Permanent Ineff=
       T       T
#Block Obstruct= 1 ,-1
 6980.65 7122.58   81.36
Bank Sta=5644.3,5824.82
XS Rating Curve= 0
Exp/Cntr=.3,.1

Type RM Length L Ch R = 1 ,20173   ,85.14,86.65,88.4
BEGIN DESCRIPTION:
Surveyed Cross-Section/XS1
END DESCRIPTION:
XS GIS Cut Line= 6
     3054367.201    13808756.308     3052920.717     13804385.18
     3053136.501     13803263.63     3053173.436     13803057.94
     3053647.213      13800423.8     3053726.044    13799280.579
#Sta/Elev= 30
       0   80.97 3572.24   82.79  3922.4   79.95 5029.59   80.87 5786.96   78.41
 5851.56   74.84 5884.68   65.99 5899.92   64.65 5915.15   64.82 5930.39   69.58
 5934.86   76.78 5940.46   78.54 5991.36    76.8 6372.38    80.8 6509.54   78.05
 6540.02    80.2 6844.84   81.22 7073.45   79.09 7970.03   80.21 8018.37   78.26
 8064.09    69.7 8170.77   81.79 8551.31   78.75 8642.62   81.19 8853.58   79.13
 9064.08   81.36 9120.86   79.05 9275.58   81.57 9379.83   79.11  9777.7    81.1
#Mann= 3 , 0 , 0
       0     .15       0 5786.96     .04       0 5940.46     .15       0
#XS Ineff= 2 , 0
       0    5576            6041       0
Permanent Ineff=
       T       T
#Block Obstruct= 1 ,-1
 7948.39 8141.94   79.93
Bank Sta=5786.96,5940.46
XS Rating Curve= 0
Exp/Cntr=.5,.3

Type RM Length L Ch R = 1 ,20087   ,120.2,121.73,121.02
BEGIN DESCRIPTION:
Copied cross-section 20173/XS2
END DESCRIPTION:
XS GIS Cut Line= 6
     3054458.284    13808748.816     3053008.384     13804379.42
     3053220.095     13803279.04      3053257.03     13803073.35
     3053774.284    13800429.848     3053879.816    13799289.118
#Sta/Elev= 30
       0   81.02 2256.13   79.83 3488.86   82.24 5796.54   77.75 5863.92   64.65
 5879.15   64.82 5912.82   74.69  5938.6   77.99 6244.86   80.78 6397.71      78
 6519.98   80.35 7050.73   78.87 7114.65   81.17 7406.48   80.88 7467.62   79.08
 7907.21   81.74 8073.39   79.71 8124.52   70.71 8150.09   71.37 8188.44   79.42
 8290.71   81.28 8559.15   78.36 8659.33   81.32 8840.11   78.86 8939.91   81.19
 9141.39   79.14 9337.22   81.39 9394.92   79.29 9472.79   81.32 9772.45   80.24
#Mann= 3 , 0 , 0
       0     .15       0 5796.54     .04       0  5938.6     .15       0
#XS Ineff= 2 , 0
       0    5558            6017       0
Permanent Ineff=
       T       T
#Block Obstruct= 1 ,-1
 8038.71 8232.26   80.18
Bank Sta=5796.54,5938.6
XS Rating Curve= 0
Exp/Cntr=.5,.3

Type RM Length L Ch R = 3 ,20024   ,,,
BEGIN DESCRIPTION:
KIRKWOOD bridges. (2 roadway bridges and 2 pipeline crossings) Pier sizes are from the Pipelines' Piers, which are larger.  The piers from the pipelines are offset in the direction of flow.  Therefore 4 sets of pipeline piers (1.5'x1.5') are modeled.
END DESCRIPTION:
Bridge Culvert--1,0,-1,-1, 0
Deck Dist Width WeirC Skew NumUp NumDn MinLoCord MaxHiCord MaxSubmerge Is_Ogee
5.865,110,2.6,0, 5, 5, , , .95, 0, 0,0,,
 5796.54 5822.72 5867.57 5912.42  5938.6
   77.75   78.23    78.3   78.21   77.99
     -.3   75.26   75.23   75.23     -.3
 5760.06 5778.14 5822.99 5867.84 5885.92
   78.05   78.23    78.3   78.21   77.38
     -.3   75.26   75.23   75.23     -.3
Pier Skew, UpSta & Num, DnSta & Num=  ,5848.81, 2 ,5809.11, 2 , 0 , 0 , 0 ,,
     1.5     1.5
       0      76
     1.5     1.5
       0      76
Pier Skew, UpSta & Num, DnSta & Num=  ,5852.81, 2 ,5813.11, 2 , 0 , 0 , 0 ,,
     1.5     1.5
       0    76.4
     1.5     1.5
       0    76.4
Pier Skew, UpSta & Num, DnSta & Num=  ,5878.81, 2 ,5839.11, 2 , 0 , 0 , 0 ,,
     1.5     1.5
       0    76.4
     1.5     1.5
       0    76.4
Pier Skew, UpSta & Num, DnSta & Num=  ,5882.81, 2 ,5843.11, 2 , 0 , 0 , 0 ,,
     1.5     1.5
       0    76.4
     1.5     1.5
       0    76.4
BR Coef=-1 , 1 , 1 ,1.25, 0 ,,,.8,-1,2,0,
WSPro=,,,, 1 ,,,, 0 ,,,, 0 ,,,,-1 ,-1 ,-1 , 0 , 0 , 0 , 0 , 0
BC Design=,, 0 ,, 0 ,,,,,,

Type RM Length L Ch R = 1 ,19965   ,85.14,85.95,83.97
BEGIN DESCRIPTION:
Copied cross-section 19769/XS3
END DESCRIPTION:
XS GIS Cut Line= 5
     3054587.534    13808748.851      3053132.15     13804371.29
      3053338.11     13803300.79     3053375.045      13803095.1
     3053855.386    13800693.312
#Sta/Elev= 30
       0    81.3   59.38   79.75  865.55   80.79   960.4      79  1172.9   79.27
 1292.35   81.29 1529.46   79.54 2240.79   81.03 2304.02   79.86 2335.63   81.71
 3426.33   82.36 4193.45   80.16  4627.2   80.95  4993.8   77.71 5038.44   80.36
 5129.11   80.72  5238.2   80.03 5268.75   77.35 5345.13   79.95 5513.15   79.53
 5564.66   76.67 5620.08   78.43 5760.06   78.05 5800.41    68.3 5806.43   63.35
 5824.22   62.11 5844.68    63.4 5849.34    67.6 5885.92   77.38 8361.62   80.68
#Mann= 3 , 0 , 0
       0     .15       0 5760.06     .04       0 5885.92     .15       0
#XS Ineff= 2 , 0
       0    5545            6009       0
Permanent Ineff=
       T       T
Bank Sta=5760.06,5885.92
XS Rating Curve= 0
Exp/Cntr=.5,.3

Type RM Length L Ch R = 1 ,19879   ,109.71,110.03,110.84
BEGIN DESCRIPTION:
Copied cross-section 19769/XS4
END DESCRIPTION:
XS GIS Cut Line= 5
     3054675.078    13808741.628     3053219.817     13804365.53
     3053421.704      13803316.2     3053458.639     13803110.51
     3053888.688    13800893.487
#Sta/Elev= 30
       0   80.46  857.96   81.39  952.81   78.23  1142.5   80.91 1237.35   78.08
 1332.19   81.33  1553.5   78.67 1735.28   81.35 2138.38   78.12 2660.04   81.95
    2992   79.32 3446.54   81.62 4444.77   77.81 4868.54   80.78 4955.95   77.32
 5123.98   80.85 5252.85   77.53  5432.2   79.91 5547.49   76.83 5719.61    77.5
 5765.41    68.3 5771.43   63.35 5789.22   62.11 5809.68    63.4 5814.34    67.6
 5856.44   77.27 6590.11   81.38 6865.15   78.45 6956.82   81.22 8147.63   81.31
#Mann= 3 , 0 , 0
       0     .15       0 5719.61     .04       0 5856.44     .15       0
#XS Ineff= 2 , 0
       0    5526            6003       0
Permanent Ineff=
       T       T
Bank Sta=5719.61,5856.44
XS Rating Curve= 0
Exp/Cntr=.3,.1

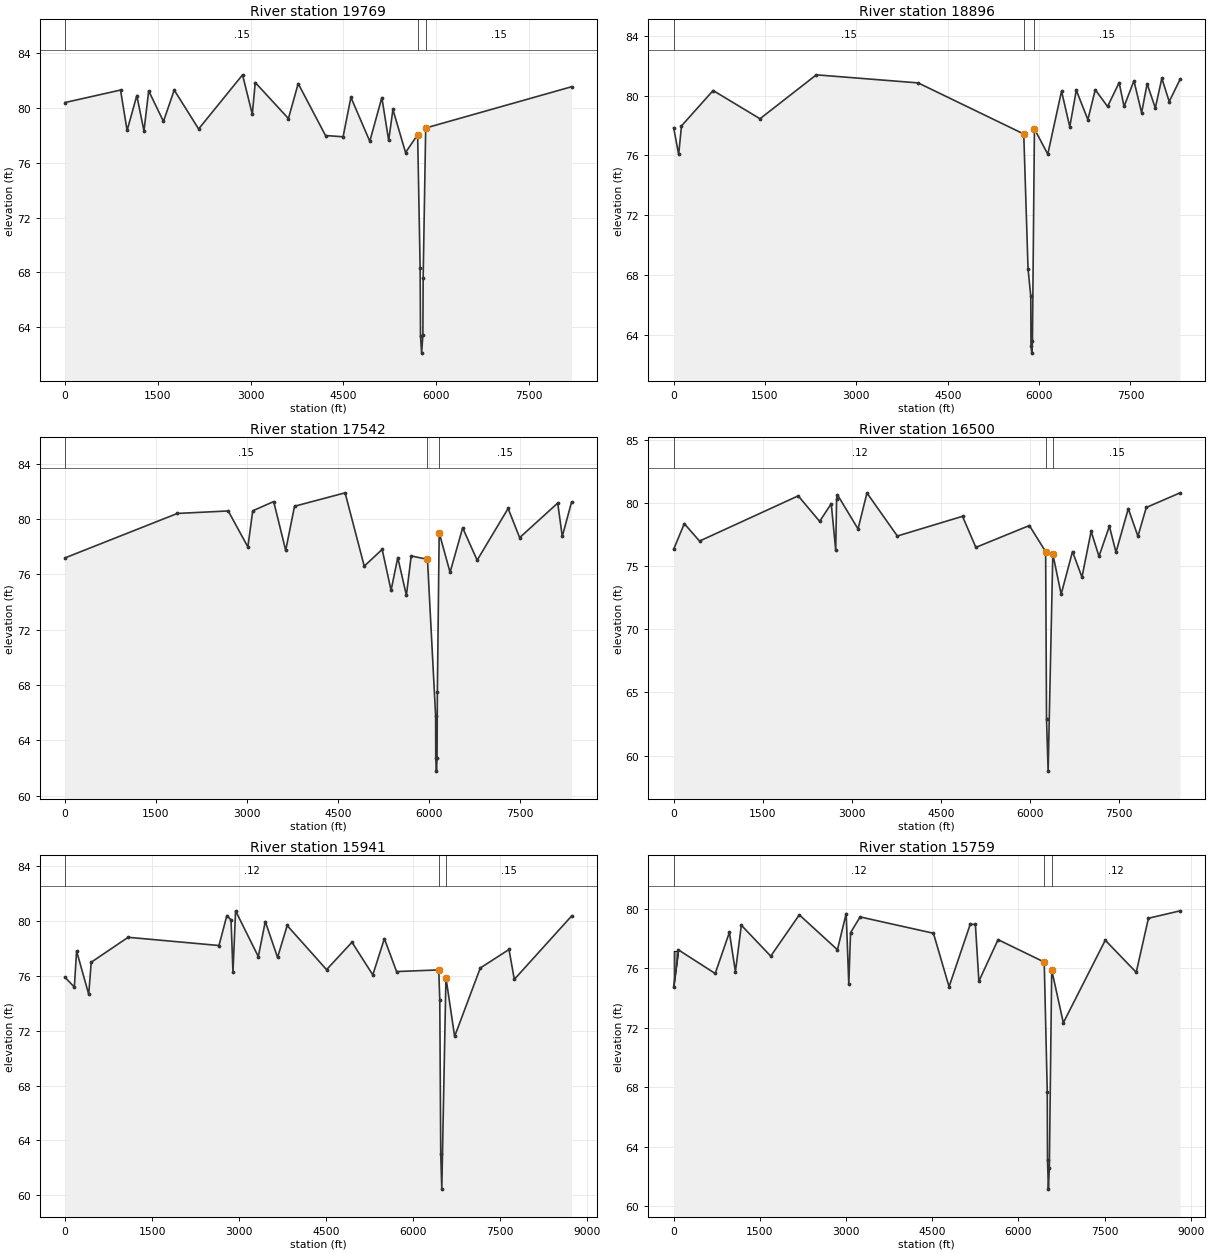
Type RM Length L Ch R = 1 ,19769   ,969.8,873.37,773.55
BEGIN DESCRIPTION:
Surveyed Cross-Section
END DESCRIPTION:
XS GIS Cut Line= 5
     3054775.082     13808749.18     3053330.175    13804358.274
     3053529.527    13803336.081     3053566.462    13803130.391
     3054021.218    13800855.424
#Sta/Elev= 30
       0    80.4  896.61   81.31  1002.8   78.36 1159.97   80.91  1275.6   78.32
 1351.92   81.25 1591.21   79.02 1765.13   81.31 2159.91   78.47 2870.52   82.42
 3028.43   79.54  3075.8   81.86 3612.71   79.23 3770.62   81.78 4212.77   77.99
 4497.02    77.9 4623.32   80.78 4928.97   77.57 5123.93   80.76 5234.62   77.63
 5302.97   79.89 5507.58   76.75 5703.06   78.05 5743.41    68.3 5749.43   63.35
 5767.22   62.11 5787.68    63.4 5792.34    67.6 5833.25   78.54 8192.94   81.55
#Mann= 3 , 0 , 0
       0     .15       0 5703.06     .04       0 5833.25     .15       0
#XS Ineff= 2 , 0
       0    5516            6022       0
Permanent Ineff=
       T       T
Bank Sta=5703.06,5833.25
XS Rating Curve= 0
Exp/Cntr=.3,.1

Type RM Length L Ch R = 1 ,18896   ,1358.9,1354.09,1344.91
BEGIN DESCRIPTION:
Surveyed Cross-Section
END DESCRIPTION:
XS GIS Cut Line= 4
       3056145.7    13808696.114     3054436.996    13803207.422
     3054364.404    13803016.615      3054641.37    13800670.022
#Sta/Elev= 30
       0   77.86   82.34   76.07  128.51   77.98   647.9   80.35 1417.69   78.46
 2342.63    81.4 4014.23   80.86 5748.72   77.44 5818.99   68.41 5863.79   66.59
 5867.51   63.27  5879.8   62.77 5891.05   63.57 5923.69   77.78 6143.09   76.09
 6368.95   80.31 6504.05   77.92 6611.32   80.37 6801.26    78.4 6922.84    80.4
 7124.86   79.28 7314.62   80.88 7395.68   79.28 7557.79      81 7683.71   78.86
 7773.95    80.8 7909.04   79.18    8016   81.17 8136.83   79.61 8315.55    81.1
#Mann= 3 , 0 , 0
       0     .15       0 5748.72     .04       0 5923.69     .15       0
#XS Ineff= 2 , 0
       0    5593            6194       0
Permanent Ineff=
       T       T
Bank Sta=5748.72,5923.69
XS Rating Curve= 0
Exp/Cntr=.3,.1

Type RM Length L Ch R = 1 ,17542   ,903.49,1041.5,1052.62
BEGIN DESCRIPTION:
Surveyed Cross-Section
END DESCRIPTION:
XS GIS Cut Line= 5
     3056749.516    13808675.678      3056454.25    13805059.455
     3055706.099    13802814.617      3055668.02    13802607.989
     3054930.062    13800583.714
#Sta/Elev= 30
       0   77.19 1853.11    80.4 2692.11   80.58 3016.66   77.98  3096.8   80.59
 3442.75   81.26 3640.86   77.73 3786.68   80.92 4621.15   81.89 4937.37   76.59
 5233.27    77.8 5380.08   74.84 5490.76   77.21 5633.06   74.48 5712.11   77.33
  5980.9   77.08 6115.61   65.76 6117.67   62.69  6129.6   61.77 6139.09   62.72
 6144.29   67.49 6174.24      79 6354.12   76.14 6561.67   79.36 6801.16   77.02
 7312.06   80.76 7502.67   78.65  8130.8   81.15 8206.08   78.74 8359.18   81.22
#Mann= 3 , 0 , 0
       0     .15       0  5980.9     .04       0 6174.24     .15       0
#XS Ineff= 2 , 0
       0    5876            6379       0
Permanent Ineff=
       T       T
Bank Sta=5980.9,6174.24
XS Rating Curve= 0
Exp/Cntr=.3,.1

Type RM Length L Ch R = 1 ,16500   ,640.73,558.61,583.67
BEGIN DESCRIPTION:
Surveyed Cross-Section
END DESCRIPTION:
XS GIS Cut Line= 5
     3056936.426    13808669.351     3056655.579    13804080.579
     3056679.475    13802429.296     3056657.086    13802299.992
     3055943.312     13800280.79
#Sta/Elev= 30
       0   76.34  179.21   78.37  435.33   76.99 2095.76   80.57 2456.44   78.55
  2651.8   79.95 2726.94   76.27 2741.97   80.33 2756.46   80.65 3102.64   77.95
  3252.7    80.8 3763.88   77.39 4860.46   78.95 5085.35   76.49 5985.58   78.22
 6259.31   76.15  6274.3   62.87 6301.18   58.77 6380.04   75.97 6520.57   72.78
 6711.48   76.16 6870.58   74.13 7024.63   77.76 7156.95   75.78 7331.96   78.17
 7442.98    76.1 7650.15   79.56 7812.11   77.37 7952.44   79.65 8521.69   80.81
#Mann= 3 , 0 , 0
       0     .12       0 6259.31     .04       0 6380.04     .15       0
#XS Ineff= 2 , 0
       0    5923            6574       0
Permanent Ineff=
       T       T
Bank Sta=6259.31,6380.04
XS Rating Curve= 0
Exp/Cntr=.3,.1

Type RM Length L Ch R = 1 ,15941   ,187.11,182.93,207.19
BEGIN DESCRIPTION:
Surveyed Cross-Section
END DESCRIPTION:
XS GIS Cut Line= 6
     3057077.775    13808664.567     3057322.911    13805839.499
     3057460.896     13804434.64     3057210.614    13802256.677
     3057058.238    13801428.586     3056380.077    13800150.214
#Sta/Elev= 30
       0   75.89  159.09   75.19  197.77   77.82  406.83   74.66  449.98      77
 1086.11   78.82    2652   78.22 2787.51    80.4 2860.02   80.08 2892.96   76.27
 2938.18   80.75 3330.06   77.41 3450.16   79.97 3661.65   77.35 3827.44   79.68
 4506.14   76.46 4944.01   78.46 5303.54   76.08 5502.66   78.72 5712.96   76.32
 6439.61   76.44 6457.43   74.27 6474.22   62.99 6492.21   60.45 6563.75   75.88
 6713.52   71.59 7155.66   76.58 7650.74   77.93 7741.97   75.75 8728.72   80.37
#Mann= 3 , 0 , 0
       0     .12       0 6439.61     .04       0 6563.75     .15       0
#XS Ineff= 2 , 0
       0    6295            6820       0
Permanent Ineff=
       T       T
Bank Sta=6439.61,6563.75
XS Rating Curve= 0
Exp/Cntr=.3,.1

Type RM Length L Ch R = 1 ,15759   ,92.55,52.75,51.76
BEGIN DESCRIPTION:
15758.49
END DESCRIPTION:
XS GIS Cut Line= 6
     3057842.516    13808625.944     3057990.737    13806028.892
     3057372.627    13802219.149     3057375.576    13802080.603
     3057386.673    13801653.645      3056678.37    13800011.467
#Sta/Elev= 30
       0   74.75   83.58   77.25  723.39   75.66  970.02   78.43 1075.19   75.78
 1178.21   78.91 1689.88   76.83    2187   79.61 2850.89   77.26 3002.85    79.7
 3048.44   74.93 3078.84   78.41 3245.99   79.47  4521.8   78.37 4793.88   74.77
 5160.71   78.96 5251.89   78.97 5312.67   75.14 5646.42   77.94 6450.15   76.43
 6502.93    67.7 6507.16   63.08 6523.06   61.14 6539.07   62.59  6580.4    75.9
 6782.58   72.34  7512.4    77.9 8051.48   75.74 8263.84   79.38 8814.94   79.88
#Mann= 3 , 0 , 0
       0     .12       0 6450.15     .04       0  6580.4     .12       0
#XS Ineff= 2 , 0
       0    6376            6905       0
Permanent Ineff=
       T       T
#Block Obstruct= 1 ,-1
       0   72.55   77.18
Bank Sta=6450.15,6580.4
XS Rating Curve= 0
Exp/Cntr=.5,.3

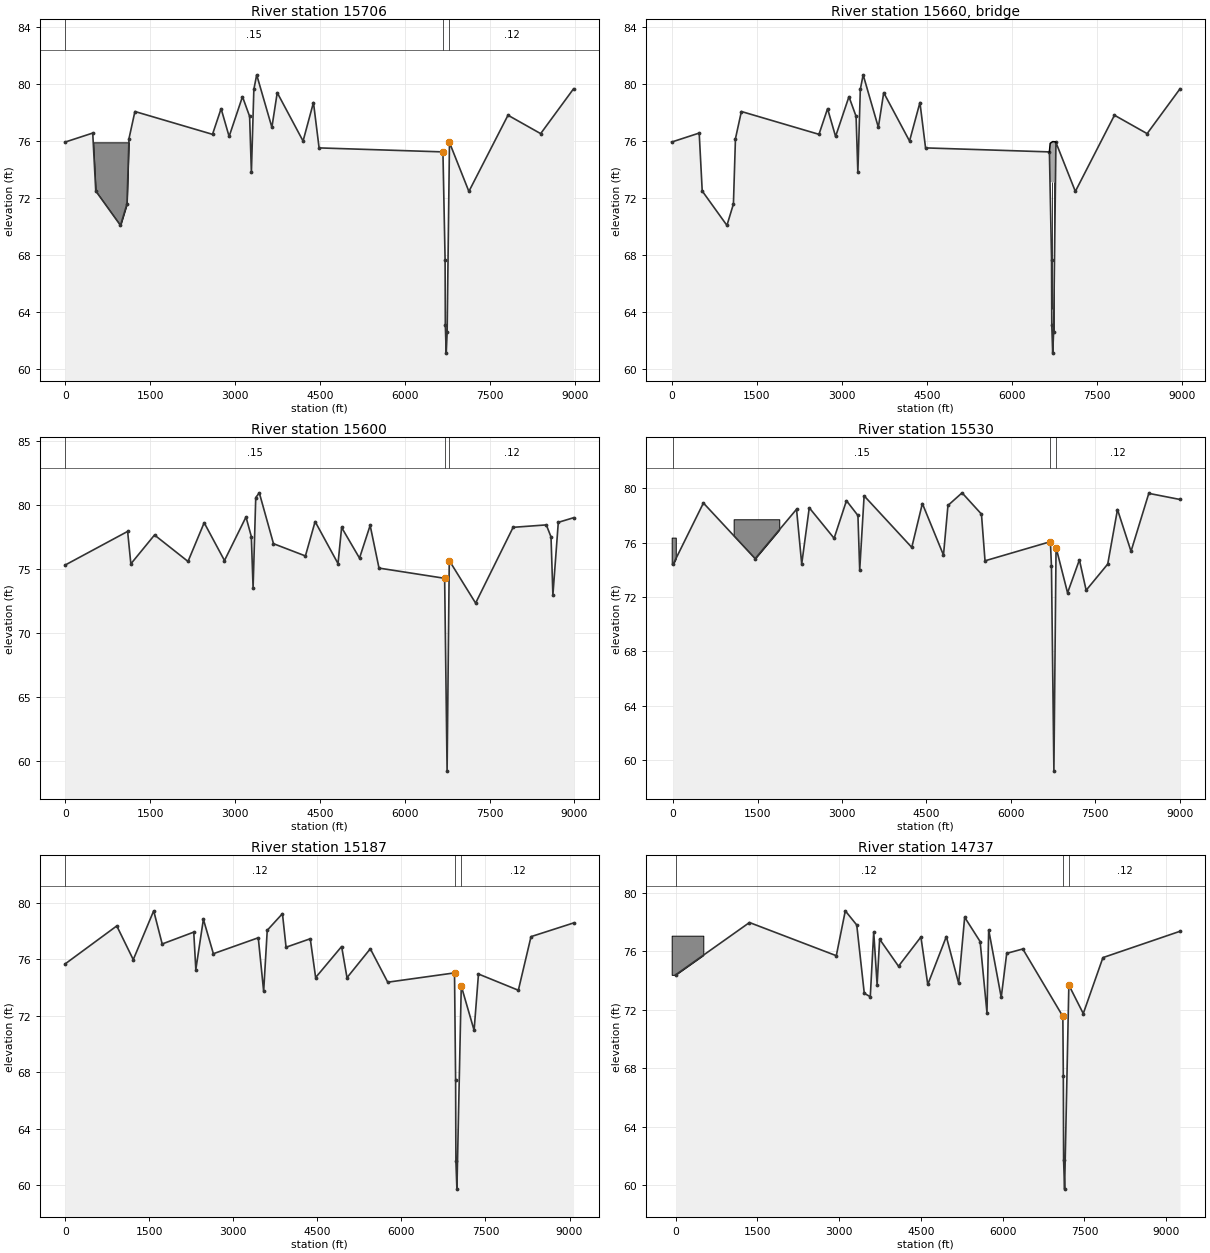
Type RM Length L Ch R = 1 ,15706   ,132.21,105.82,81.41
BEGIN DESCRIPTION:
S 15705.74
END DESCRIPTION:
XS GIS Cut Line= 6
     3058406.304    13808675.153     3058598.641     13805958.25
     3057422.791    13802212.007     3057425.562    13802081.784
     3057436.557    13801658.755     3056954.788     13799960.04
#Sta/Elev= 30
       0   75.93  485.76   76.56     539    72.5  975.09   70.09 1089.62   71.59
 1125.46   76.17 1230.06   78.07 2599.14   76.47 2750.69   78.27 2892.19   76.32
 3127.91   79.11 3253.78   77.73 3285.22    73.8 3328.58   79.62 3378.66   80.64
 3646.82   76.96 3741.15   79.39 4197.07      76 4380.43    78.7 4479.81   75.52
 6664.97   75.24 6702.93    67.7 6707.16   63.08 6723.06   61.14 6739.07   62.59
  6780.4    75.9 7122.84   72.47 7812.95   77.81 8389.28   76.52 8969.29   79.66
#Mann= 3 , 0 , 0
       0     .15       0 6664.97     .04       0  6780.4     .12       0
#XS Ineff= 2 , 0
       0    6570            7020       0
Permanent Ineff=
       F       F
#Block Obstruct= 1 ,-1
  471.58 1136.64   75.91
Bank Sta=6664.97,6780.4
XS Rating Curve= 0
Exp/Cntr=.5,.3

Type RM Length L Ch R = 3 ,15660   ,,,
BEGIN DESCRIPTION:
Wilcrest Bridge
END DESCRIPTION:
Bridge Culvert--1,0,-1,-1, 0
Deck Dist Width WeirC Skew NumUp NumDn MinLoCord MaxHiCord MaxSubmerge Is_Ogee
10.41,85,2.6,0, 5, 5, , , .95, 0, 0,0,,
 6664.97 6678.64 6722.59 6766.54  6780.4
   75.24   75.84   75.96   75.95    75.9
     -.3   73.13   73.11    73.1     -.3
 6687.61 6704.24 6748.19 6792.14  6797.9
   76.08   75.84   75.96   75.95    75.6
     -.3   73.13   73.11    73.1     -.3
Pier Skew, UpSta & Num, DnSta & Num=  ,6706.09, 2 ,6731.69, 2 , 0 , 0 , 0 ,,
    1.35    1.35
       0      75
    1.35    1.35
       0      75
Pier Skew, UpSta & Num, DnSta & Num=  ,6739.09, 2 ,6764.69, 2 , 0 , 0 , 0 ,,
    1.35    1.35
       0      75
    1.35    1.35
       0      75
BR Coef=-1 , 1 , 1 ,1.25, 0 ,,,.8,-1,2,0,
WSPro=,,,, 1 ,,,, 0 ,,,, 0 ,,,,-1 ,-1 ,-1 , 0 , 0 , 0 , 0 , 0
BC Design=,, 0 ,, 0 ,,,,,,

Type RM Length L Ch R = 1 ,15600   ,70.58,70.08,72.14
BEGIN DESCRIPTION:
S 15599.92
END DESCRIPTION:
XS GIS Cut Line= 5
     3058510.723    13808683.465     3058688.641     13805929.75
     3057547.996    13802162.946     3057512.402    13802060.955
     3057308.346    13799889.328
#Sta/Elev= 30
       0    75.3 1103.26   77.93 1160.34   75.39 1578.53   77.65 2170.48   75.58
 2456.08   78.61 2815.15   75.65 3195.42   79.06 3289.45   77.53  3320.8   73.51
 3367.82   80.58 3430.51   80.95 3681.27   76.97 4245.48   76.01 4417.14    78.7
 4821.78   75.41 4885.41   78.24 5201.52   75.84 5389.59    78.4 5546.31   75.06
 6706.28   74.26 6749.64   59.17 6788.05   75.65 7253.63   72.32 7916.53   78.25
 8503.25   78.44 8586.39    77.5 8619.65   72.95 8715.04   78.64 8984.39      79
#Mann= 3 , 0 , 0
       0     .15       0 6706.28     .04       0 6788.05     .12       0
#XS Ineff= 2 , 0
       0    6590            7040       0
Permanent Ineff=
       F       F
Bank Sta=6706.28,6788.05
XS Rating Curve= 0
Exp/Cntr=.5,.3

Type RM Length L Ch R = 1 ,15530   ,361.42,342.7,338.15
BEGIN DESCRIPTION:
15529.84
END DESCRIPTION:
XS GIS Cut Line= 5
     3058577.717    13808662.861     3058755.635    13805909.145
      3057614.99    13802142.341     3057579.396     13802040.35
     3057449.769     13799844.33
#Sta/Elev= 30
       0    74.4  539.48   78.93  1458.4   74.83 2193.29   78.47 2285.11   74.43
  2419.2   78.58 2860.44   76.33 3079.85    79.1  3283.6   78.01 3314.94   73.98
 3393.31   79.46 4239.63   75.66  4427.7   78.89 4802.89   75.09  4882.2   78.75
 5132.97   79.68 5477.29   78.11 5540.45   74.67 6701.61   76.08 6720.28   74.26
 6763.64   59.17 6802.05   75.65  7006.4   72.31 7216.76   74.74  7336.5    72.5
 7719.75   74.43 7892.94   78.45 8133.35   75.37  8448.9   79.64 9003.03   79.19
#Mann= 3 , 0 , 0
       0     .15       0 6701.61     .04       0 6802.05     .12       0
#XS Ineff= 2 , 0
       0    6571            7091       0
Permanent Ineff=
       F       F
#Block Obstruct= 2 ,-1
  -24.18   48.37   76.38 1076.18 1886.34   77.73
Bank Sta=6701.61,6802.05
XS Rating Curve= 0
Exp/Cntr=.3,.1

Type RM Length L Ch R = 1 ,15187   ,497.2,450.48,420.01
BEGIN DESCRIPTION:
S 15187.14
END DESCRIPTION:
XS GIS Cut Line= 6
     3059078.785      13808742.6     3059175.666     13805364.92
     3057937.114    13802018.108     3057891.056    13801906.648
     3057861.182    13801084.997     3057623.334    13799927.898
#Sta/Elev= 30
       0   75.69  920.48   78.38 1214.49   75.99 1579.19   79.45 1730.81    77.1
 2293.99   77.94 2331.06   75.29 2466.11   78.85 2644.09   76.41 3445.51   77.54
 3541.59   73.74 3605.57   78.07 3877.15   79.25 3941.45   76.87 4373.29   77.47
 4469.25   74.72 4933.09   76.92 5029.05   74.71  5444.9   76.76 5756.04   74.39
  6947.7   75.05 6967.25   67.44 6972.67   61.69 6990.49   59.72  7068.3   74.12
 7297.37   70.98 7375.25   74.97 8087.02   73.82 8313.04   77.62 9071.79   78.59
#Mann= 3 , 0 , 0
       0     .12       0  6947.7     .04       0  7068.3     .12       0
#XS Ineff= 2 , 0
       0    6790            7340       0
Permanent Ineff=
       F       F
Bank Sta=6947.7,7068.3
XS Rating Curve= 0
Exp/Cntr=.3,.1

Type RM Length L Ch R = 1 ,14737   ,501.18,669.44,689.24
BEGIN DESCRIPTION:
14736.66
END DESCRIPTION:
XS GIS Cut Line= 6
      3059463.44     13808816.56     3059510.597     13805419.32
     3058404.637     13801944.23     3058312.372      13801772.8
      3058269.63     13801085.93     3057672.745     13799902.43
#Sta/Elev= 30
       0   74.38 1354.79   77.96 2947.71   75.69 3112.73   78.76 3322.67   77.79
 3460.73   73.12 3570.92   72.88 3633.88   77.32 3696.31   73.71 3742.49   76.82
 4088.83   74.97 4499.66   76.97 4625.59   73.72 4966.24      77 5192.27   73.79
 5302.46   78.32 5585.81   76.66 5711.74   71.78 5743.22   77.46 5973.24   72.84
 6073.79   75.85 6368.94   76.15  7103.6   71.54 7112.25   67.44 7117.67   61.69
 7135.49   59.72 7213.91   73.68  7478.2   71.73 7838.89   75.56 9252.78   77.36
#Mann= 3 , 0 , 0
       0     .12       0  7103.6     .04       0 7213.91     .12       0
#XS Ineff= 2 , 0
       0    6810            7450       0
Permanent Ineff=
       F       F
#Block Obstruct= 1 ,-1
  -72.55  507.86   77.06
Bank Sta=7103.6,7213.91
XS Rating Curve= 0
Exp/Cntr=.3,.1

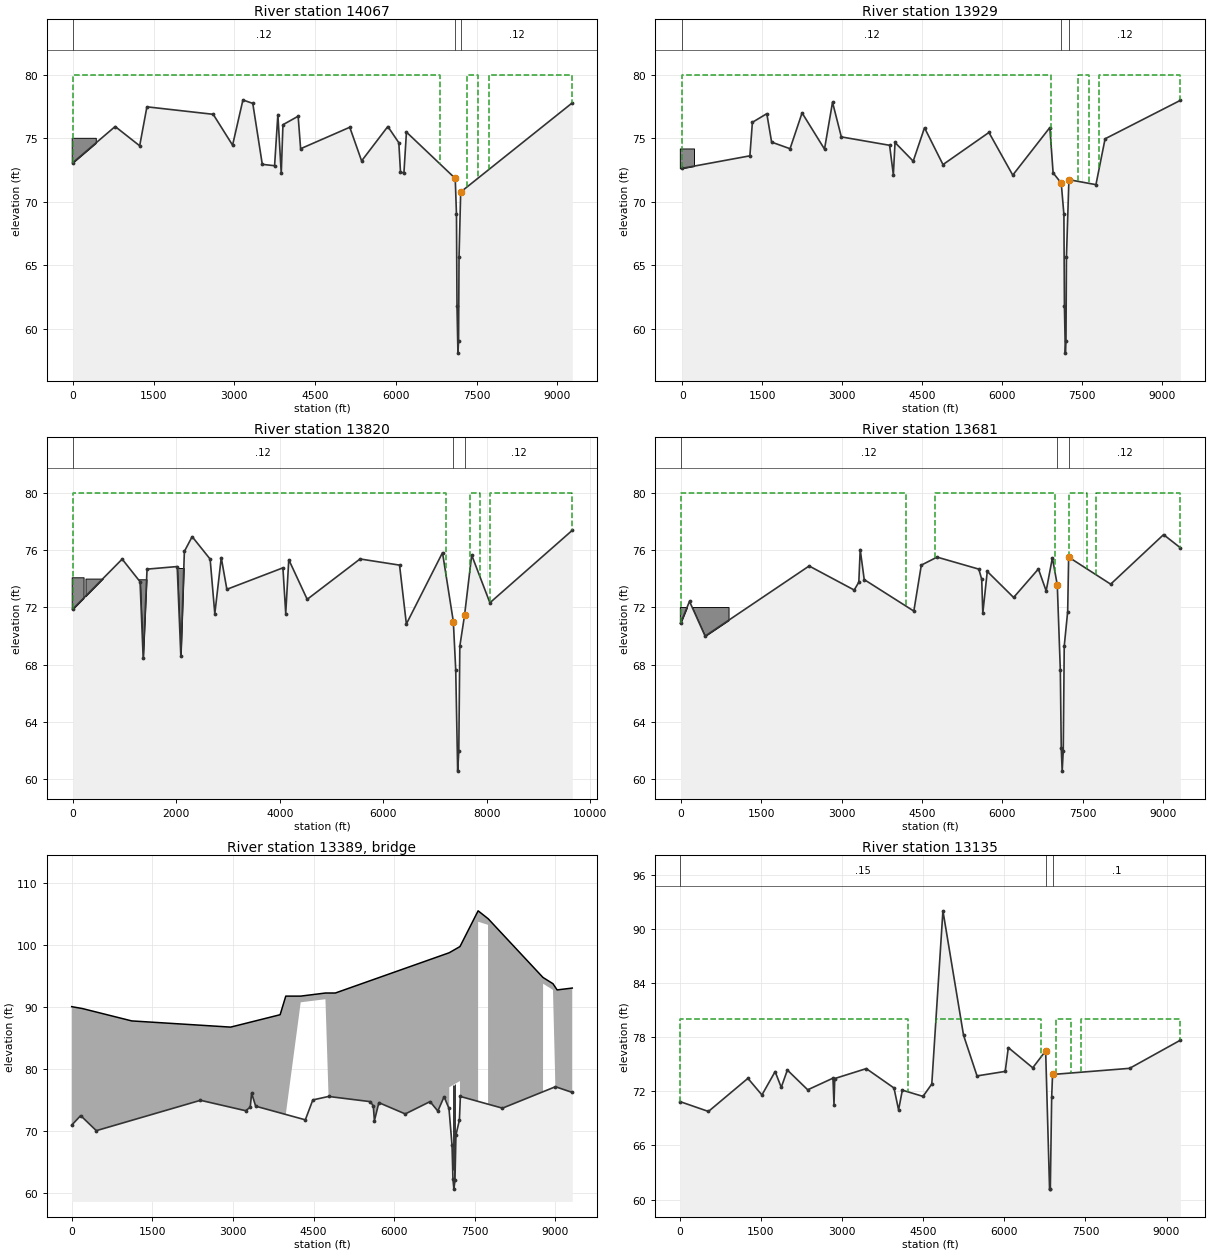
Type RM Length L Ch R = 1 ,14067   ,203.52,137.96,30.7
BEGIN DESCRIPTION:
14067.22
END DESCRIPTION:
XS GIS Cut Line= 5
     3059768.884    13808820.794     3059932.387     13805038.63
      3058947.49    13801901.023       3059021.1    13801697.267
      3057798.32    13800128.935
#Sta/Elev= 30
       0   73.09  783.79   75.93 1239.45   74.41 1373.86   77.48 2605.73   76.89
 2966.06   74.46 3158.45   78.02 3341.41   77.75 3518.24   72.95 3746.79   72.84
 3807.84   76.87 3870.73   72.23 3902.17   76.07 4184.78   76.74 4230.61   74.18
 5144.19   75.87 5364.29   73.22 5851.66   75.93 6056.04   74.65 6086.69   72.37
 6150.37   72.25 6197.54   75.49 7104.61   71.84 7127.37      69 7137.17   61.76
 7154.63   58.08 7166.45   59.06 7175.09   65.64 7205.88   70.77 9279.58   77.79
#Mann= 3 , 0 , 0
       0     .12       0 7104.61     .04       0 7205.88     .12       0
#XS Ineff= 3 ,-1
       0    6825      80    7325    7525      80    7725 9279.58      80
Permanent Ineff=
       T       T       T
#Block Obstruct= 1 ,-1
  -24.18  423.22   75.04
Bank Sta=7104.61,7205.88
XS Rating Curve= 0
Exp/Cntr=.3,.1

Type RM Length L Ch R = 1 ,13929   ,149.69,109.45,113.68
BEGIN DESCRIPTION:
13929.26
END DESCRIPTION:
XS GIS Cut Line= 6
      3059880.65     13808832.82     3060058.195    13806154.474
     3060118.563    13805284.889     3060155.913      13804689.8
     3059083.413    13801742.486     3057816.896     13800125.22
#Sta/Elev= 30
       0   72.64 1266.19   73.62  1313.2   76.26 1583.79   76.94 1673.99    74.7
 2019.74   74.18 2245.24      77 2666.16   74.15 2816.52   77.84 2981.91   75.11
 3887.13   74.45 3957.84   72.13 3989.14   74.67  4330.2    73.2 4542.31   75.83
 4888.88   72.93 5750.84   75.46 6197.79    72.1  6893.9   75.85 6954.87   72.28
 7107.63   71.47 7157.37      69 7167.17   61.76 7184.63   58.08 7196.45   59.06
 7205.09   65.64 7251.29   71.74 7758.49   71.35 7929.96   74.96 9342.71   77.99
#Mann= 3 , 0 , 0
       0     .12       0 7107.63     .04       0 7251.29     .12       0
#XS Ineff= 3 ,-1
       0    6922      80    7422    7622      80    7822 9342.71      80
Permanent Ineff=
       T       T       T
#Block Obstruct= 1 ,-1
  -48.37  217.65    74.2
Bank Sta=7107.63,7251.29
XS Rating Curve= 0
Exp/Cntr=.3,.1

Type RM Length L Ch R = 1 ,13820   ,186.99,138.91,152.62
BEGIN DESCRIPTION:
13819.82
END DESCRIPTION:
XS GIS Cut Line= 6
     3060005.444    13808847.213      3060166.19    13806279.212
      3060593.22    13804389.155     3060426.083     13803720.61
     3059193.518    13801749.086     3057831.756    13800121.505
#Sta/Elev= 30
       0   71.89  951.57   75.37 1297.25   73.79 1357.36   68.48 1432.51   74.67
 2014.83   74.85 2085.55    68.6 2153.92   75.91 2304.21   76.94 2651.77   75.37
 2742.23   71.55 2866.81   75.47 2975.12   73.26 4058.75   74.76 4112.98   71.57
 4171.95   75.33 4527.91   72.56 5549.78   75.38  6313.2   74.95 6445.12   70.84
 7143.49   75.82 7352.79   71.01 7399.06   67.64 7436.64   60.56 7458.43   61.96
 7478.34   69.29 7570.19   71.46 7707.74   75.65 8059.78   72.32 9651.77   77.38
#Mann= 3 , 0 , 0
       0     .12       0 7352.79     .04       0 7570.19     .12       0
#XS Ineff= 3 ,-1
       0    7217      80    7667    7867      80    8070 9651.77      80
Permanent Ineff=
       T       T       T
#Block Obstruct= 4 ,-1
  -24.18  205.56    74.1  241.84  906.89   74.01  1197.1 1426.84   73.96
 1983.07    2237   74.75
Bank Sta=7352.79,7570.19
XS Rating Curve= 0
Exp/Cntr=.5,.3

Type RM Length L Ch R = 1 ,13681   ,640.11,546,572.11
BEGIN DESCRIPTION:
13680.90
END DESCRIPTION:
XS GIS Cut Line= 6
     3060366.677    13808888.529     3060585.578    13806049.756
     3061107.485    13804247.732     3060876.066    13803585.615
     3059330.517    13801748.772     3057802.035    13800054.634
#Sta/Elev= 30
       0   70.88 167.136   72.42 457.951   69.992396.755   74.893236.357   73.21
3322.608   73.763348.502   76.043423.229   73.944347.802   71.74 4487.25   74.95
4780.191   75.515559.205   74.675612.788   73.965633.306   71.595716.344   74.51
6207.581   72.696669.049   74.686814.028   73.156930.058   75.467021.142   73.57
7077.817   67.64 7095.39   62.16 7112.41   60.567132.468   61.967150.794   69.29
7215.037   71.717232.922   75.518016.189   73.629001.902   77.089315.398   76.16
#Mann= 3 , 0 , 0
       0     .12       07021.142     .04       07232.922     .12       0
#XS Ineff= 4 ,-1
       04197.502      804749.805 6982.95      807239.771 7566.55      80
7750.6519315.398      80
Permanent Ineff=
       T       T       T       T
#Block Obstruct= 2 ,-1
 -13.357 120.209   72.02 173.635 894.906   72.02
Bank Sta=7021.142,7232.922
XS Rating Curve= 0
Skew Angle= 23
Exp/Cntr=.5,.3

Type RM Length L Ch R = 3 ,13389   ,,,
BEGIN DESCRIPTION:
Hwy 59
END DESCRIPTION:
Bridge Culvert--1,0,-1,-1, 0
Deck Dist Width WeirC Skew NumUp NumDn MinLoCord MaxHiCord MaxSubmerge Is_Ogee
116.5,313,2.6,23, 22, 19, , , .95, 0, 0,0,,
       0   196.8  1117.3 2958.31 3878.81 3983.95 4261.94 4722.19 4906.29 7026.02
 7026.02 7225.96 7225.96 7563.22  7563.6  7747.7 7748.62  8771.3 8772.22 8956.32
 9033.649315.398
      90    89.7    87.7    86.7    88.7    91.7    91.7    92.2    92.2    98.7
    98.7    99.7    99.7  105.46  105.46   104.2   104.2    94.7    94.7    93.7
    92.7      93
       0     -.3     -.3     -.3     -.3     -.3    90.7    91.2     -.3     -.3
      77      78     -.3     -.3   103.7   103.2     -.3     -.3    93.7    92.7
     -.3       0
       0 2674.07 3958.17 4261.94 4722.19 4786.63 6741.87 6741.87 6947.97 6947.97
 7233.04 7233.42 7417.52 7418.44 8671.16 8672.08 8856.18  8933.5 9256.15
      89    88.7    91.7    91.7    92.2    92.2    98.7    98.7    99.7    99.7
  105.46  105.46   104.2   104.2    94.7    94.7    93.7    92.7      93
       0     -.3     -.3    90.7    91.2     -.3     -.3      77      78     -.3
     -.3   103.7   103.2     -.3     -.3    93.7    92.7     -.3       0
Pier Skew, UpSta & Num, DnSta & Num=  ,7090.649, 2 ,6815.418, 2 , 0 , 0 , 0 ,,
     2.5     2.5
     -.3      78
     2.5     2.5
     -.3      79
Pier Skew, UpSta & Num, DnSta & Num=  ,7113.662, 2 ,6838.431, 2 , 0 , 0 , 0 ,,
     2.5     2.5
       0      78
     2.5     2.5
       0      78
Pier Skew, UpSta & Num, DnSta & Num=  ,7136.674, 2 ,6861.443, 2 , 0 , 0 , 0 ,,
     2.5     2.5
       0      79
     2.5     2.5
       0      79
BR Coef=-1 , 1 , 1 ,1.25, 0 ,,,.8,-1,2,0,
WSPro=,,,, 1 ,,,, 0 ,,,, 0 ,,,,-1 ,-1 ,-1 , 0 , 0 , 0 , 0 , 0
BC Design=,, 0 ,, 0 ,,,,,,

Type RM Length L Ch R = 1 ,13135   ,86.98,210.99,291.42
BEGIN DESCRIPTION:
13134.90
END DESCRIPTION:
XS GIS Cut Line= 6
      3060677.83       13808858.     3061236.005     13803596.18
     3059892.628     13802004.66     3059912.572     13801977.89
     3059781.998     13801822.94     3058145.071      13800006.2
#Sta/Elev= 30
       0   70.86 529.152   69.761258.993   73.431518.336   71.591762.334   74.18
1875.584   72.431988.834   74.352365.062   72.162831.933   73.452850.896   70.53
2864.777   73.41 3447.76   74.513960.325   72.364045.278   69.934114.758   72.12
4496.989   71.434659.236    72.84865.154      925246.335   78.215495.875    73.7
6016.963    74.26074.081   76.84  6525.8    74.6 6764.91   76.476837.087   61.15
6851.115   61.196876.107   71.35 6892.52   73.868317.259   74.549256.154   77.66
#Mann= 3 , 0 , 0
       0     .15       0 6764.91     .04       0 6892.52      .1       0
#XS Ineff= 4 ,-1
       04215.912      804731.3956671.819      806957.1767235.168      80
7419.2699256.154      80
Permanent Ineff=
       T       T       T       T
Bank Sta=6764.91,6892.52
XS Rating Curve= 0
Skew Angle= 23
Exp/Cntr=.5,.3