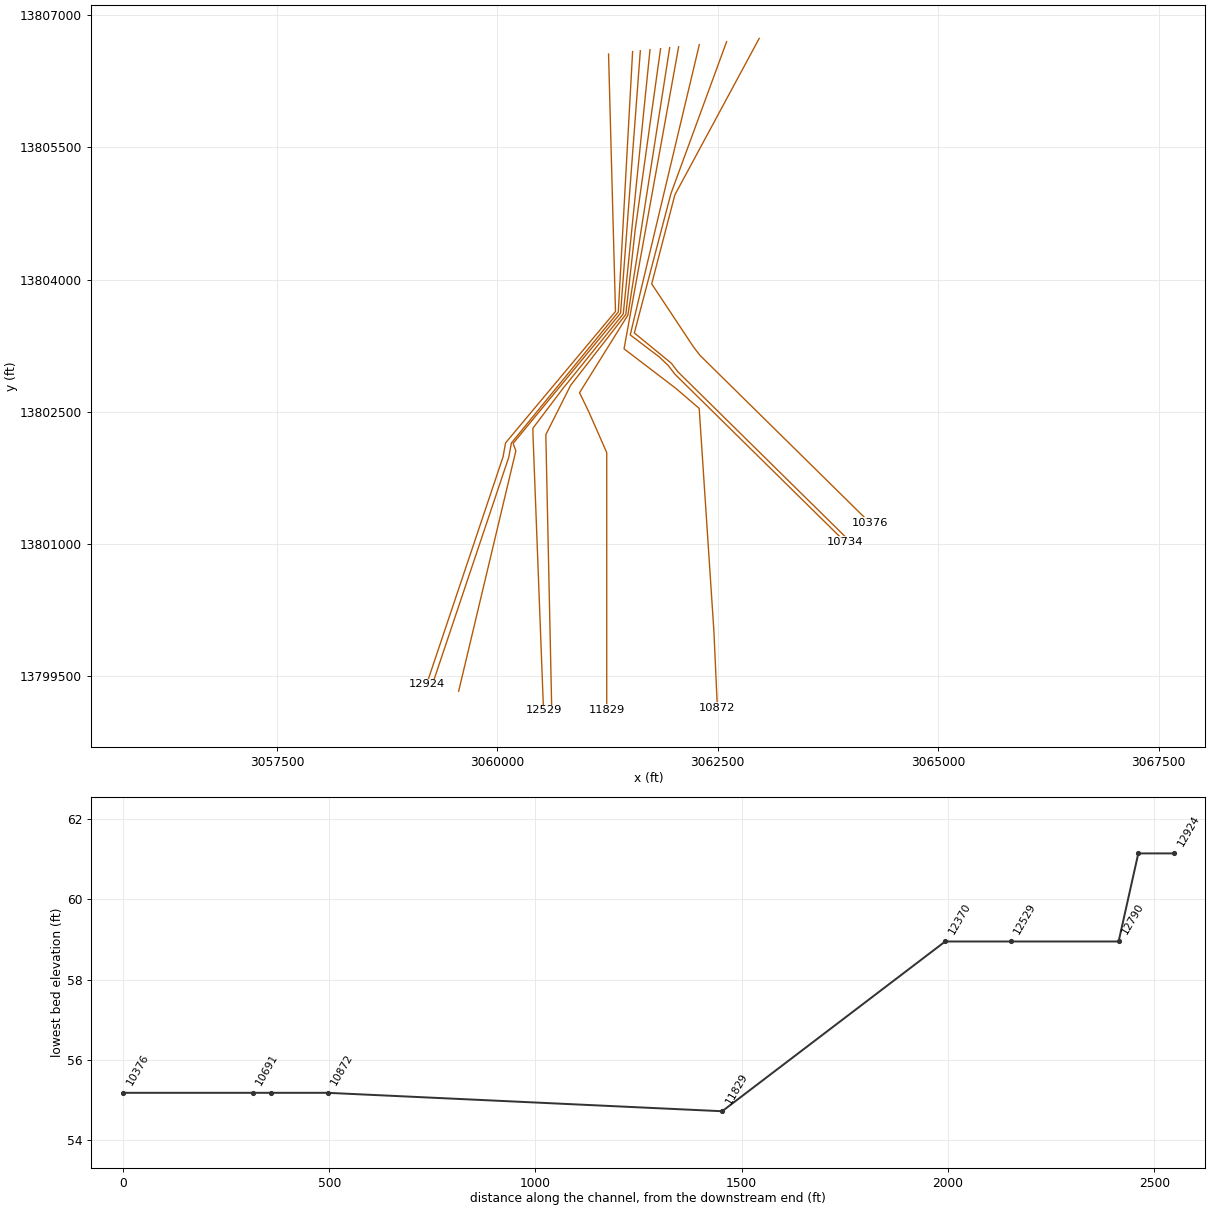
HEC-RAS study D118-00-00.prj: D118-00-00

--- D118-00-00.g03 (geometry) --- (continued)

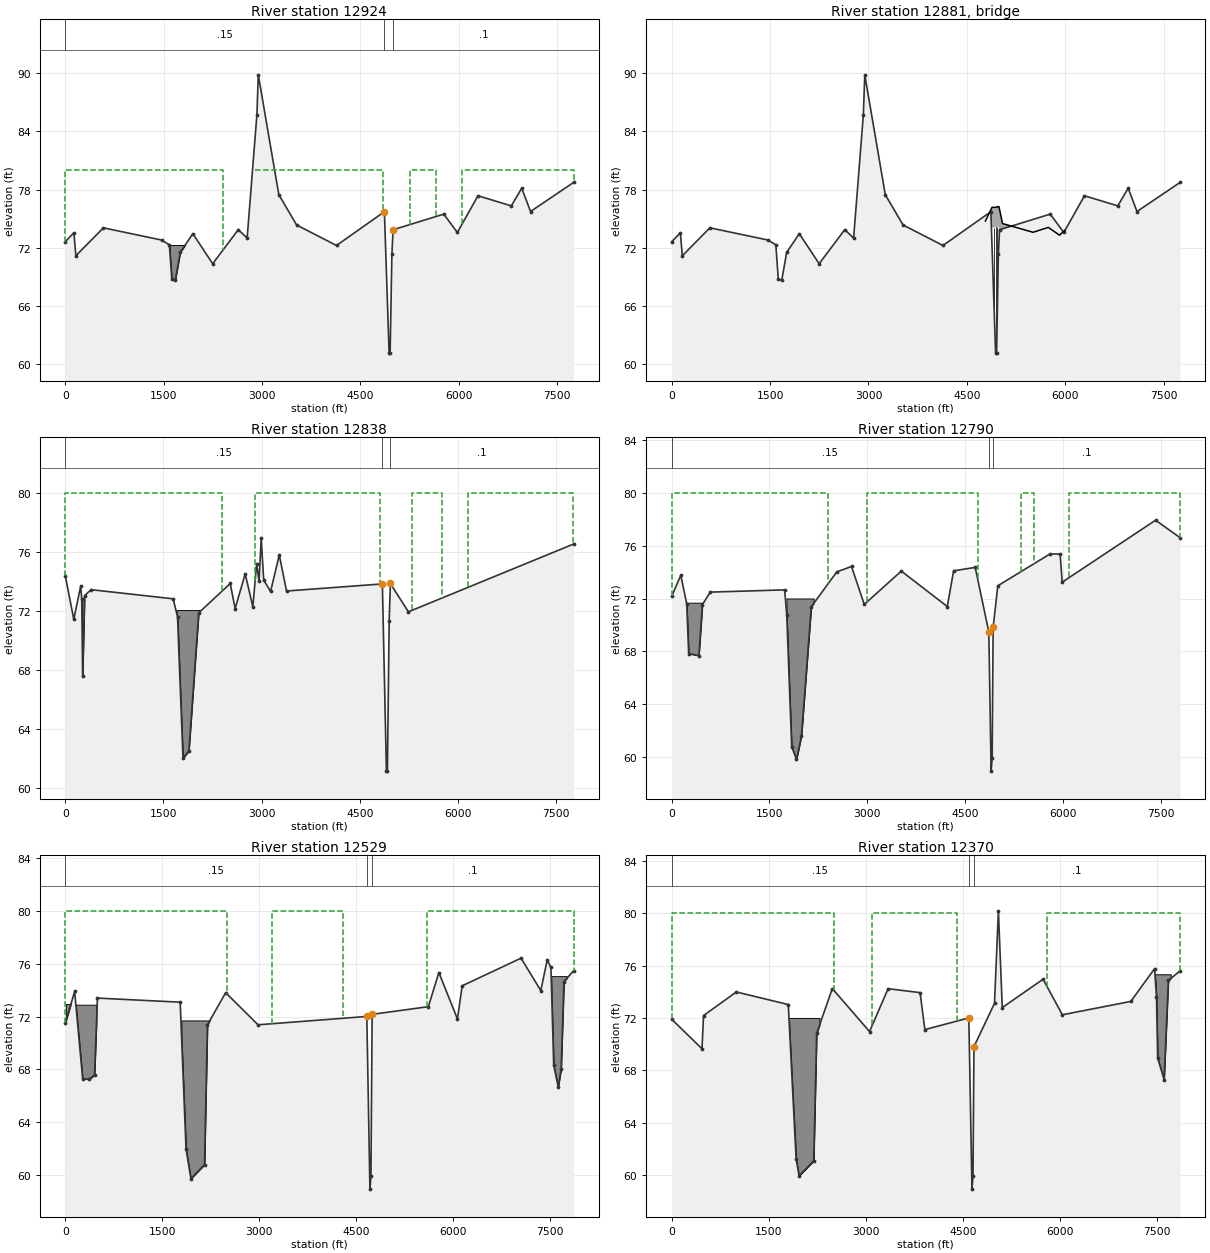
Type RM Length L Ch R = 1 ,12924   ,98.93,86.28,95.57
BEGIN DESCRIPTION:
S 12923.91
END DESCRIPTION:
XS GIS Cut Line= 5
     3061262.158    13806559.808     3061340.668     13803638.84
     3060094.399    13802147.682     3060064.992    13801987.351
     3059198.814    13799408.861
#Sta/Elev= 30
       0   72.62  132.36   73.55  162.37   71.18  582.52   74.06 1467.84    72.8
 1587.88   72.31 1624.59   68.79 1677.91   68.66 1752.94   71.53 1946.06   73.45
 2248.12   70.36 2638.26   73.87 2773.31      73 2922.02   85.71 2943.32   89.82
  3256.1   77.47 3527.32   74.35 4135.47   72.24 4865.41   75.72 4937.54   61.15
 4952.78   61.19 4979.93   71.35 4997.76   73.86 5770.83   75.47 5977.67   73.58
 6292.37   77.36 6800.51   76.32 6958.75   78.14 7093.15   75.74  7748.5   78.73
#Mann= 3 , 0 , 0
       0     .15       0 4865.41     .04       0 4997.76      .1       0
#XS Ineff= 4 ,-1
       0    2400      80    2900    4850      80    5250    5650      80
    6050  7748.5      80
Permanent Ineff=
       T       T       T       T
#Block Obstruct= 1 ,-1
 1596.13 1857.32   72.29
Bank Sta=4865.41,4997.76
XS Rating Curve= 0
Exp/Cntr=.5,.3

Type RM Length L Ch R = 3 ,12881   ,,,
BEGIN DESCRIPTION:
Roark Bridge
END DESCRIPTION:
Bridge Culvert--1,0,-1,-1, 0
Deck Dist Width WeirC Skew NumUp NumDn MinLoCord MaxHiCord MaxSubmerge Is_Ogee
27.74,30.8,2.6,0, 11, 11, , , .95, 0, 0,0,,
 4782.24 4883.43 4883.43 4935.93 4988.43 4988.43  5042.8  5507.8  5741.8  5911.8
  5991.8
   74.76   76.17   76.17   76.17   76.25   76.25    74.5    73.6    74.1    73.3
    73.8
       0       0   74.09   74.09   74.17       0       0       0       0       0
       0
 4750.73 4851.92 4851.92 4904.42 4956.92 4956.92 5011.29 5476.29 5710.29 5880.29
 5960.29
   74.76   76.17   76.17   76.17   76.25   76.25    74.2    73.6    74.1    73.3
    73.8
       0       0   74.09   74.09   74.17       0       0       0       0       0
       0
Pier Skew, UpSta & Num, DnSta & Num=  ,4914, 2 ,4882, 2 , 0 , 0 , 0 ,,
     1.4     1.4
     -.3      75
     1.4     1.4
     -.3      75
Pier Skew, UpSta & Num, DnSta & Num=  ,4938, 2 ,4906, 2 , 0 , 0 , 0 ,,
     1.4     1.4
       0      75
     1.4     1.4
       0      75
Pier Skew, UpSta & Num, DnSta & Num=  ,4961, 2 ,4929, 2 , 0 , 0 , 0 ,,
     1.4     1.4
       0      75
     1.4     1.4
       0      75
BR Coef=-1 , 1 , 1 ,1.25, 0 ,,,.8,-1,2,0,
WSPro=,,,, 1 ,,,, 0 ,,,, 0 ,,,,-1 ,-1 ,-1 , 0 , 0 , 0 , 0 , 0
BC Design=,, 0 ,, 0 ,,,,,,

Type RM Length L Ch R = 1 ,12838   ,29.24,47.71,86
BEGIN DESCRIPTION:
12837.63
END DESCRIPTION:
XS GIS Cut Line= 5
     3061534.833    13806588.309     3061372.619    13803632.757
     3060160.045    13802145.898     3060130.638    13801985.568
      3059264.46    13799407.077
#Sta/Elev= 30
       0    74.4  131.01   71.44  236.16   73.67   252.7   72.79  266.21   67.57
  296.25   73.04  395.76   73.44 1648.29   72.82 1715.04   71.61 1798.51   62.02
 1888.65   62.53 2038.87   71.87  2519.6   73.86 2594.71   72.16 2748.22   74.51
 2865.12   72.28 2923.06   75.21    2960   74.02 2992.59   76.92 3030.92   74.09
 3135.84   73.32 3268.73   75.79 3379.71   73.35 4842.76   73.83 4904.54   61.15
 4919.78   61.19 4946.93   71.35 4964.76   73.86 5239.89   71.94 7761.71   76.53
#Mann= 3 , 0 , 0
       0     .15       0 4842.76     .04       0 4964.76      .1       0
#XS Ineff= 4 ,-1
       0    2400      80    2900    4800      80    5300    5750      80
    6150  7748.5      80
Permanent Ineff=
       T       T       T       T
#Block Obstruct= 2 ,-1
  232.16  309.55    72.8 1702.54 2050.79   72.06
Bank Sta=4842.76,4964.76
XS Rating Curve= 0
Exp/Cntr=.5,.3

Type RM Length L Ch R = 1 ,12790   ,93.43,261.36,214.6
BEGIN DESCRIPTION:
12789.92
END DESCRIPTION:
XS GIS Cut Line= 6
     3061622.518    13806597.474     3061398.485    13803620.591
     3060252.756    13802230.453     3060179.948    13802142.114
     3060210.674    13802057.204      3059561.95    13799329.661
#Sta/Elev= 30
       0   72.18  140.37   73.76  230.62   71.61  260.71   67.84  417.46   67.69
   471.3   71.54  591.64   72.49 1732.52   72.66 1764.95   70.76 1840.16   60.81
 1913.99   59.83 1990.59   61.62 2141.01   71.39 2532.04   74.02 2757.75   74.43
  2953.3   71.56 3521.43   74.08 4226.86    71.4 4323.31    74.1  4654.5   74.36
 4863.39   69.48 4898.78   58.95 4914.67   59.94 4929.62   69.82 5001.49   72.97
 5802.78   75.38 5957.43   75.36 5988.27   73.24 7421.17   77.93 7795.14   76.61
#Mann= 3 , 0 , 0
       0     .15       0 4863.39     .04       0 4929.62      .1       0
#XS Ineff= 4 ,-1
       0    2400      80    3000    4700      80    5350    5550      80
    6100 7795.14      80
Permanent Ineff=
       T       T       T       T
#Block Obstruct= 2 ,-1
  212.82     474   71.69 1760.58 2176.54   72.01
Bank Sta=4863.39,4929.62
XS Rating Curve= 0
Exp/Cntr=.3,.1

Type RM Length L Ch R = 1 ,12529   ,178.32,159.02,146.1
BEGIN DESCRIPTION:
12528.56
END DESCRIPTION:
XS GIS Cut Line= 6
     3061732.262    13806608.945     3061428.915    13803611.466
     3060748.434     13802769.51     3060403.936      13802313.7
      3060405.45    13802225.795     3060524.361     13799111.03
#Sta/Elev= 30
       0   71.49  146.26    73.9  270.35   67.29  371.03   67.26  453.76   67.57
  498.99    73.4 1780.48   73.09    1871   61.99 1946.38   59.74 2157.45   60.81
 2202.68   71.38 2484.78   73.81 2986.62   71.38 4670.54   72.01 4718.78   58.95
 4734.67   59.94 4752.92   72.17 5623.55   72.75 5786.36   75.33 6073.88   71.82
 6147.83   74.33 7058.75   76.42 7364.82   73.97  7463.6   76.28 7521.43   75.72
 7564.81   68.31 7635.02   66.68 7680.05   68.04 7723.86   74.65 7871.66   75.46
#Mann= 3 , 0 , 0
       0     .15       0 4670.54     .04       0 4752.92      .1       0
#XS Ineff= 3 ,-1
       0    2500      80    3200    4300      80    5600 7871.66      80
Permanent Ineff=
       T       T       T
#Block Obstruct= 4 ,-1
    9.67  125.76   72.95  164.45  483.68    72.9 1799.27 2273.28   71.71
    7526 7767.84   75.06
Bank Sta=4670.54,4752.92
XS Rating Curve= 0
Exp/Cntr=.3,.1

Type RM Length L Ch R = 1 ,12370   ,425.56,540.71,604.84
BEGIN DESCRIPTION:
S 12369.54
END DESCRIPTION:
XS GIS Cut Line= 6
      3061852.12    13806621.473     3061564.524    13804566.435
     3061457.823    13803605.383     3060831.643     13802800.16
     3060550.533    13802240.401     3060618.538    13799077.718
#Sta/Elev= 30
       0   71.91  468.49   69.66  492.34   72.19  998.61   73.99 1801.36   73.03
 1922.53   61.26 1967.97   59.96 2194.73   61.11 2240.01   70.83 2481.48   74.25
  3056.6   70.97 3343.37   74.24 3837.41   73.94 3911.18   71.12 4590.54   72.01
 4638.78   58.95 4654.67   59.94 4669.62   69.82 4987.05   73.12 5047.07   80.18
 5107.08    72.8 5737.23   74.96 6035.32   72.25 7092.83   73.27 7460.02   75.77
  7489.4   73.61 7507.63   68.94  7606.9   67.31 7672.67   74.87  7852.5   75.59
#Mann= 3 , 0 , 0
       0     .15       0 4590.54     .04       0 4669.62      .1       0
#XS Ineff= 3 ,-1
       0    2500      80    3100    4400      80    5800  7852.5      80
Permanent Ineff=
       T       T       T
#Block Obstruct= 2 ,-1
 1808.95 2282.95   72.01 7458.28 7709.79   75.34
Bank Sta=4590.54,4669.62
XS Rating Curve= 0
Exp/Cntr=.3,.1

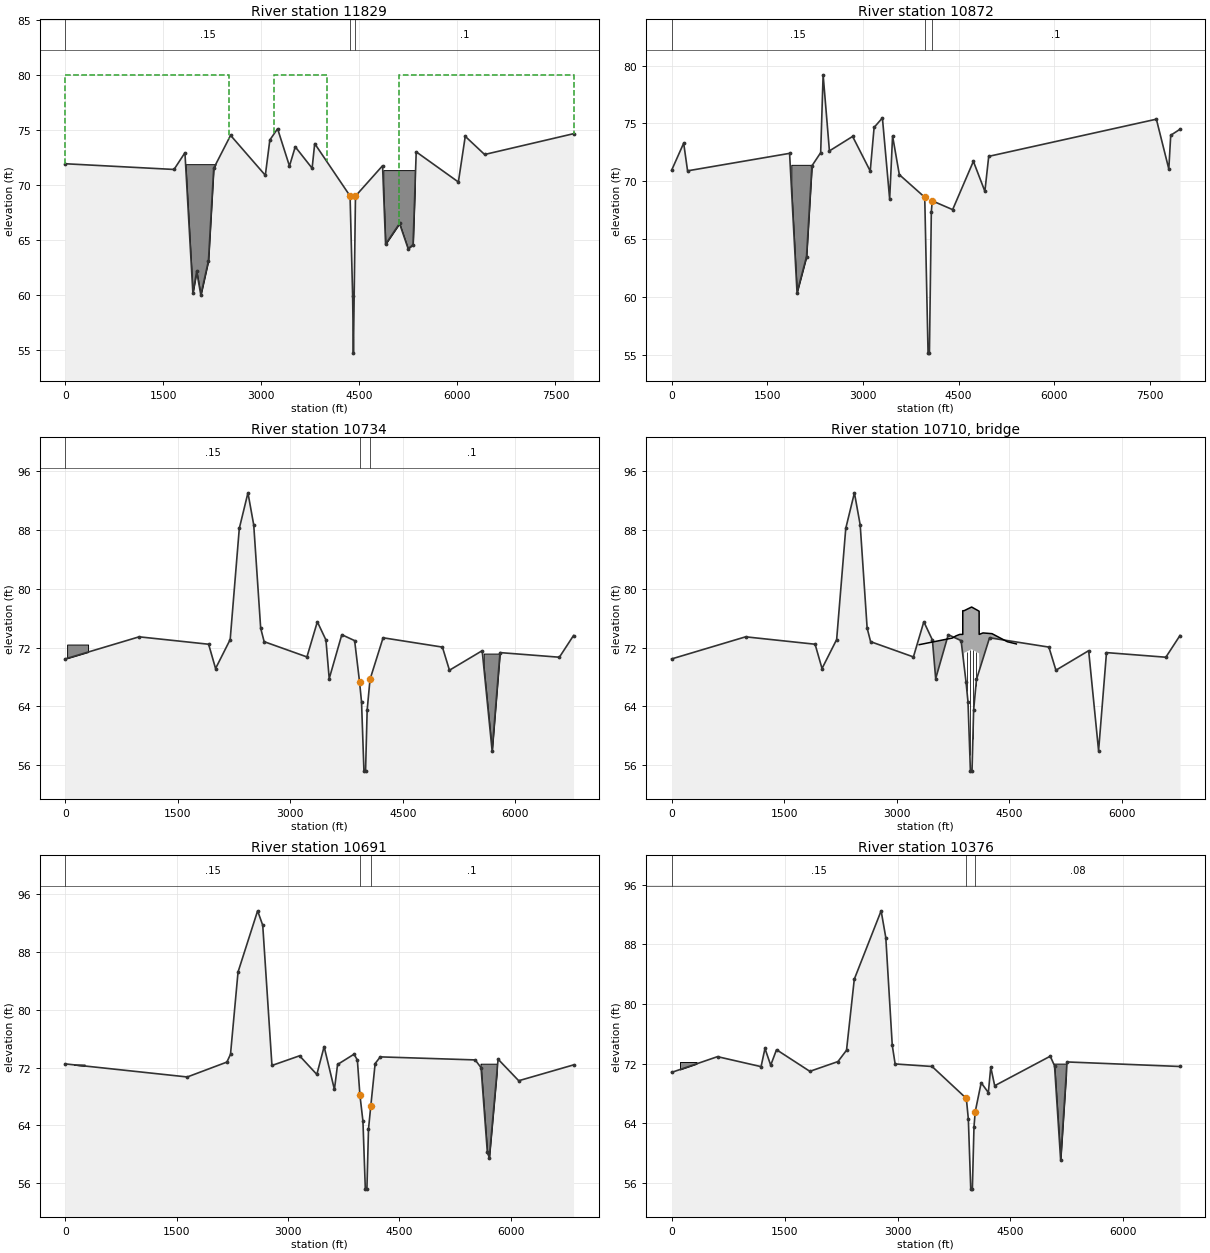
Type RM Length L Ch R = 1 ,11829   ,835.24,956.53,1008.61
BEGIN DESCRIPTION:
S 11828.83
END DESCRIPTION:
XS GIS Cut Line= 6
     3061955.286    13806632.257     3061481.312    13803597.802
     3060933.369    13802717.113     3061041.309    13802492.431
      3061241.29    13802037.347      3061241.29    13799115.957
#Sta/Elev= 30
       0   71.92  1664.7    71.4 1831.57   72.92 1953.16   60.17 2011.49   62.14
 2074.61   59.99 2191.42   63.11 2271.98   71.51 2530.07    74.5 3061.43   70.87
 3130.49   74.08 3248.83    75.1 3430.82   71.71 3519.15   73.46 3777.26   71.51
 3816.72   73.75 4357.75   68.99 4397.18   59.89 4408.97   54.71 4440.56   68.98
  4854.9   71.74 4900.96   64.61 5114.75   66.49 5245.96    64.2 5320.96   64.56
 5369.75      73 6014.75   70.26 6119.75   74.41 6415.96   72.76 7776.29   74.65
#Mann= 3 , 0 , 0
       0     .15       0 4357.75     .04       0 4440.56      .1       0
#XS Ineff= 3 ,-1
       0    2500      80    3200    4000      80    5100 7776.29      80
Permanent Ineff=
       T       T       T
#Block Obstruct= 2 ,-1
  1828.3 2331.32   71.88 4865.78 5349.46   71.34
Bank Sta=4357.75,4440.56
XS Rating Curve= 0
Exp/Cntr=.3,.1

Type RM Length L Ch R = 1 ,10872   ,173.25,138.14,114.51
BEGIN DESCRIPTION:
10872.30
END DESCRIPTION:
XS GIS Cut Line= 6
     3062057.122    13806642.901     3061437.793    13803214.486
     3062024.788    13802766.486     3062290.041    13802538.629
     3062457.191    13800004.692     3062496.161    13799142.186
#Sta/Elev= 30
       0   70.97   188.4    73.3  249.37   70.91 1849.86   72.42 1966.73    60.4
 2115.55    63.5 2200.45   71.34 2337.63   72.48    2376    79.2 2474.82   72.63
 2838.65   73.88 3115.01   70.89 3175.95   74.66 3306.17   75.48 3419.87   68.47
  3465.6   73.92 3571.59   70.58 3970.26   68.63 4022.26   55.18 4043.66   55.17
 4073.56   67.37 4087.98   68.32 4407.91   67.56 4733.47   71.73 4913.83   69.14
 4973.95   72.16 7604.18   75.37 7799.38   71.07 7829.41   73.98 7974.87    74.5
#Mann= 3 , 0 , 0
       0     .15       0 3970.26     .04       0 4087.98      .1       0
#XS Ineff= 2 , 0
       0    2500            4350       0
Permanent Ineff=
       T       T
#Block Obstruct= 1 ,-1
 1876.66 2205.56   71.43
Bank Sta=3970.26,4087.98
XS Rating Curve= 0
Exp/Cntr=.5,.3

Type RM Length L Ch R = 1 ,10734   ,36.71,43.65,43.38
BEGIN DESCRIPTION:
10734.16
END DESCRIPTION:
XS GIS Cut Line= 6
      3062291.64    13806667.414     3061508.151    13803372.674
     3061836.443    13803123.484     3061938.952    13803025.583
     3062014.247    13802927.269     3063945.369    13801023.573
#Sta/Elev= 30
       0   70.46   985.5   73.47 1911.78   72.46 2004.29   69.15 2199.22    73.1
  2320.6   88.24    2436   93.09 2513.09   88.71  2605.6   74.65 2651.86   72.81
 3222.33   70.73  3361.1   75.52 3475.49   73.04 3519.22   67.77 3687.11   73.76
 3858.11   72.95 3923.55   67.34 3950.16   64.58 3982.26   55.18 4003.66   55.17
 4025.06   63.48 4062.94   67.66 4237.43   73.34 5028.18   72.07 5122.08   68.92
 5558.52   71.58 5690.78   57.95  5796.1   71.32 6587.39   70.69 6776.05   73.65
#Mann= 3 , 0 , 0
       0     .15       0 3923.55     .04       0 4062.94      .1       0
#XS Ineff= 2 , 0
       0    2600            4400       0
Permanent Ineff=
       T       T
#Block Obstruct= 2 ,-1
   25.39  304.72   72.42 5577.99 5823.46   71.19
Bank Sta=3923.55,4062.94
XS Rating Curve= 0
Exp/Cntr=.5,.3

Type RM Length L Ch R = 3 ,10710   ,,,
BEGIN DESCRIPTION:
Sam Houston Toll Feeder West Bridge.  Concrete Rail Length adjusted according to field Measurement.
END DESCRIPTION:
Bridge Culvert--1,0,-1,-1, 0
Deck Dist Width WeirC Skew NumUp NumDn MinLoCord MaxHiCord MaxSubmerge Is_Ogee
4.65,35,2.6,0, 15, 14, , , .95, 0, 0,0,,
    3300 3739.95 3789.95 3839.95 3880.33 3880.33 3898.33 3898.33 3998.33 4098.33
    4099    4150    4270    4475    4595
    72.4    73.3    73.6    73.8    73.8   77.03   77.03   77.03   77.53   76.96
    73.8      74    73.9    72.8    72.5
       0       0       0       0       0       0       0   71.28   71.78   71.21
       0       0       0       0       0
    3365 3851.95 3901.95 3942.33 3942.33 3960.33 3960.33 4060.33 4160.33    4161
    4215    4355    4540    4660
    71.1    73.6    73.8    73.8   77.03   77.03   77.03   77.53   76.96    73.8
      74    73.9    72.8    73.2
       0       0       0       0       0       0   71.28   71.78   71.21       0
       0       0       0       0
Pier Skew, UpSta & Num, DnSta & Num=  ,3935, 2 ,3996, 2 , 0 , 0 , 0 ,,
     1.6     1.6
     -.2    71.8
     1.6     1.6
     -.2    71.8
Pier Skew, UpSta & Num, DnSta & Num=  ,3975, 2 ,4036, 2 , 0 , 0 , 0 ,,
     1.6     1.6
       0      72
     1.6     1.6
       0      72
Pier Skew, UpSta & Num, DnSta & Num=  ,4015, 2 ,4076, 2 , 0 , 0 , 0 ,,
     1.6     1.6
       0      72
     1.6     1.6
       0      72
Pier Skew, UpSta & Num, DnSta & Num=  ,4055, 2 ,4116, 2 , 0 , 0 , 0 ,,
     1.6     1.6
       0      72
     1.6     1.6
       0      72
BR Coef=-1 , 1 , 1 ,1.25, 0 ,,,.8,-1,2,0,
WSPro=,,,, 1 ,,,, 0 ,,,, 0 ,,,,-1 ,-1 ,-1 , 0 , 0 , 0 , 0 , 0
BC Design=,, 0 ,, 0 ,,,,,,

Type RM Length L Ch R = 1 ,10691   ,354.4,314.23,311.94
BEGIN DESCRIPTION:
10690.51
END DESCRIPTION:
XS GIS Cut Line= 6
     3062600.711    13806699.719     3061968.881    13804974.133
      3061554.82    13803394.898     3061974.419     13803051.05
     3062049.714    13802952.736     3063980.835     13801049.04
#Sta/Elev= 30
       0    72.5 1644.83   70.69 2178.22   72.75 2226.99   73.83 2328.39   85.21
 2592.22   93.68 2661.18   91.68 2785.24   72.28 3157.41   73.62 3390.01   71.04
 3488.08   74.89 3626.85   68.96 3669.55   72.42 3890.88   73.84 3936.04   73.04
 3970.49   68.18 4011.16   64.58 4043.26   55.18 4064.66   55.17 4086.06   63.48
 4117.43   66.72 4175.69   72.55 4244.88   73.47 5523.73   73.05 5602.56   71.97
 5687.42   60.24  5713.3   59.54 5832.09   73.15 6109.86   70.17 6848.37   72.36
#Mann= 3 , 0 , 0
       0     .15       0 3970.49     .04       0 4117.43      .1       0
#XS Ineff= 2 , 0
       0    2720            4450       0
Permanent Ineff=
       T       T
#Block Obstruct= 2 ,-1
   118.5  262.39   72.42 5594.92 5814.99   72.53
Bank Sta=3970.49,4117.43
XS Rating Curve= 0
Exp/Cntr=.5,.3

Type RM Length L Ch R = 1 ,10376   ,48.19,46.21,45.6
BEGIN DESCRIPTION:
10376.29
END DESCRIPTION:
XS GIS Cut Line= 6
     3062971.224    13806738.447     3062013.879    13804961.276
     3061751.376    13803952.084     3062223.134    13803239.668
     3062298.429    13803141.355     3064229.551    13801237.658
#Sta/Elev= 30
       0   70.83  608.76   72.94 1187.36    71.6 1239.17   74.04 1315.16   71.79
 1392.51   73.87  1835.5   70.97 2208.52   72.28 2322.23    73.8  2425.5   83.33
 2781.98    92.5 2843.98    88.9 2929.72   74.46 2967.97   71.96 3458.77   71.62
 3913.55   67.34 3940.16   64.58 3972.26   55.18 3993.66   55.17 4015.06   63.48
 4031.46   65.54 4110.73   69.44 4205.93   68.12 4238.01   71.53 4290.18   69.04
  5028.2      73 5085.02   71.71 5166.08    59.1 5250.94   72.23 6751.38   71.62
#Mann= 3 , 0 , 0
       0     .15       0 3913.55     .04       0 4031.46     .08       0
#XS Ineff= 2 , 0
       0    2900            4400       0
Permanent Ineff=
       T       T
#Block Obstruct= 2 ,-1
  110.04  330.11   72.22  5053.2 5239.42   72.01
Bank Sta=3913.55,4031.46
XS Rating Curve= 0
Exp/Cntr=.5,.3