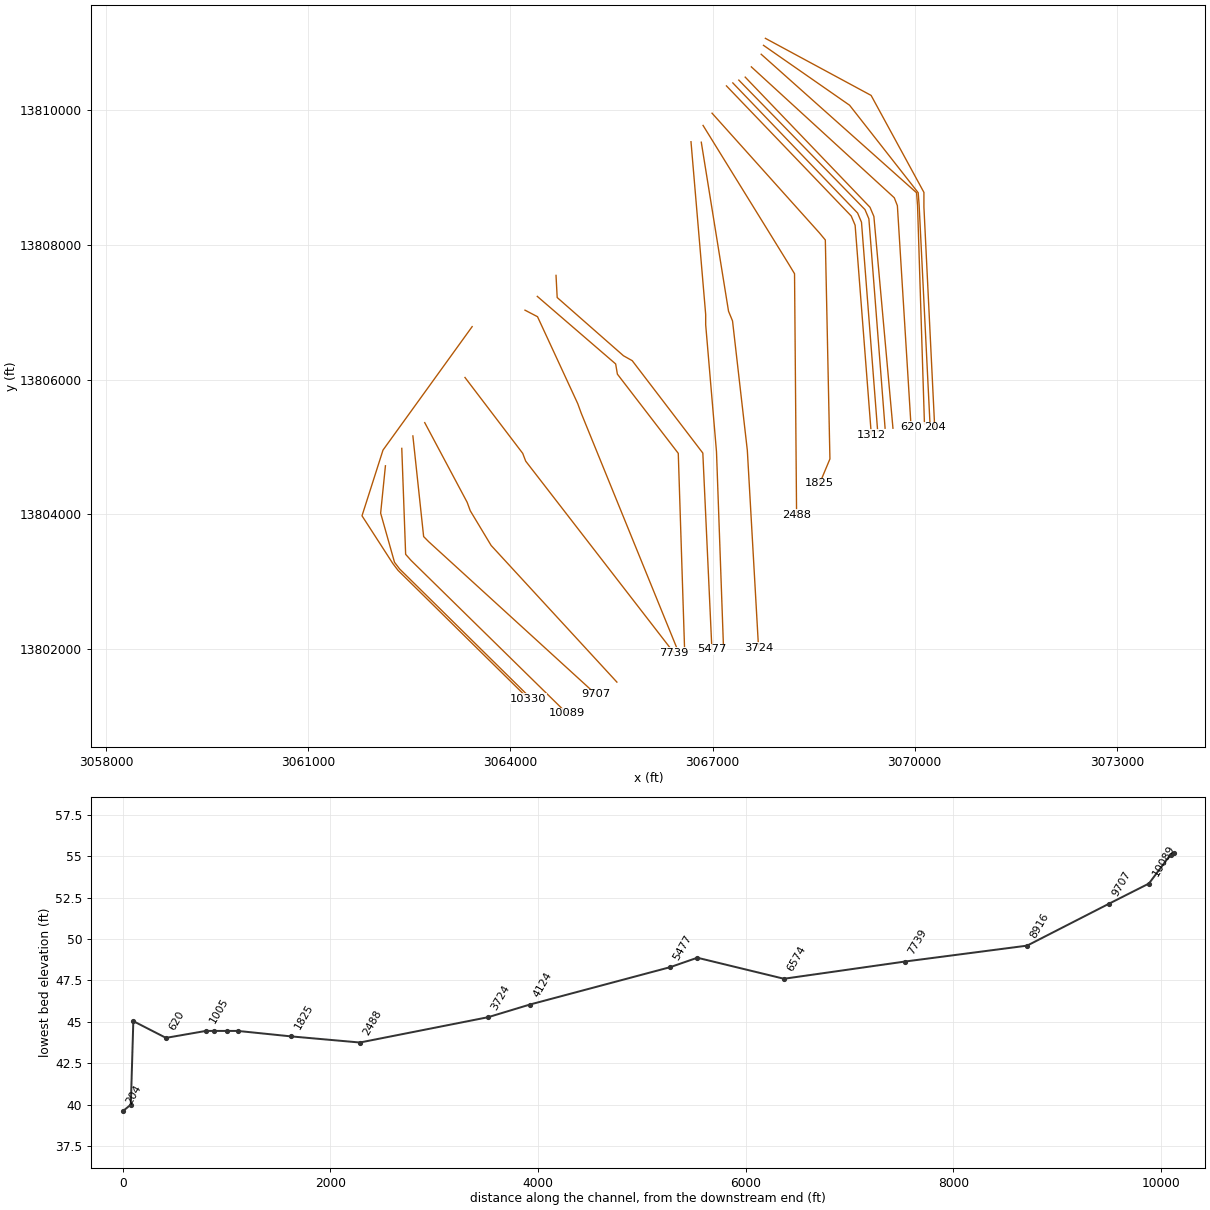
HEC-RAS study D118-00-00.prj: D118-00-00

--- D118-00-00.g03 (geometry) --- (continued)

Type RM Length L Ch R = 3 ,10370   ,,,
BEGIN DESCRIPTION:
Sam Houston Toll Feeder East Bridge. Concrete Rail Length adjusted according to field Measurement.
END DESCRIPTION:
Bridge Culvert--1,0,-1,-1, 0
Deck Dist Width WeirC Skew NumUp NumDn MinLoCord MaxHiCord MaxSubmerge Is_Ogee
5.605,35,2.6,0, 17, 17, , , .95, 0, 0,0,,
    3382 3718.95 3768.95 3818.95 3859.33 3859.33 3877.33 3877.33 3977.33 4077.33
 4077.33 4095.33 4095.33 4135.35 4185.35 4235.35    4452
    71.1    73.3    73.5    73.7    73.7   76.44   76.44   76.44   76.88   76.38
   76.38   76.38    73.7    73.7    73.5    73.3    71.1
       0       0       0       0       0       0       0   70.42   70.86   70.36
       0       0       0       0       0       0       0
    3599 3935.95 3985.95 4035.95 4076.33 4076.33 4094.33 4094.33 4194.33 4294.33
 4294.33 4312.33 4312.33 4352.35 4402.35 4452.35    4639
    71.4    73.3    73.5    73.7    73.7   76.44   76.44   76.44   76.88   76.38
   76.38   76.38    73.7    73.7    73.5    73.3      71
       0       0       0       0       0       0       0   70.42   70.86   70.36
       0       0       0       0       0       0       0
Pier Skew, UpSta & Num, DnSta & Num=  ,3916, 2 ,4133, 2 , 0 , 0 , 0 ,,
     1.6     1.6
     -.3      75
     1.6     1.6
     -.3      75
Pier Skew, UpSta & Num, DnSta & Num=  ,3956, 2 ,4173, 2 , 0 , 0 , 0 ,,
     1.6     1.6
       0      75
     1.6     1.6
       0      75
Pier Skew, UpSta & Num, DnSta & Num=  ,3996, 2 ,4213, 2 , 0 , 0 , 0 ,,
     1.6     1.6
       0      75
     1.6     1.6
       0      75
Pier Skew, UpSta & Num, DnSta & Num=  ,4036, 2 ,4253, 2 , 0 , 0 , 0 ,,
     1.6     1.6
       0      75
     1.6     1.6
       0      75
BR Coef=-1 , 1 , 1 ,1.25, 0 ,,,.8,-1,2,0,
WSPro=,,,, 1 ,,,, 0 ,,,, 0 ,,,,-1 ,-1 ,-1 , 0 , 0 , 0 , 0 , 0
BC Design=,, 0 ,, 0 ,,,,,,

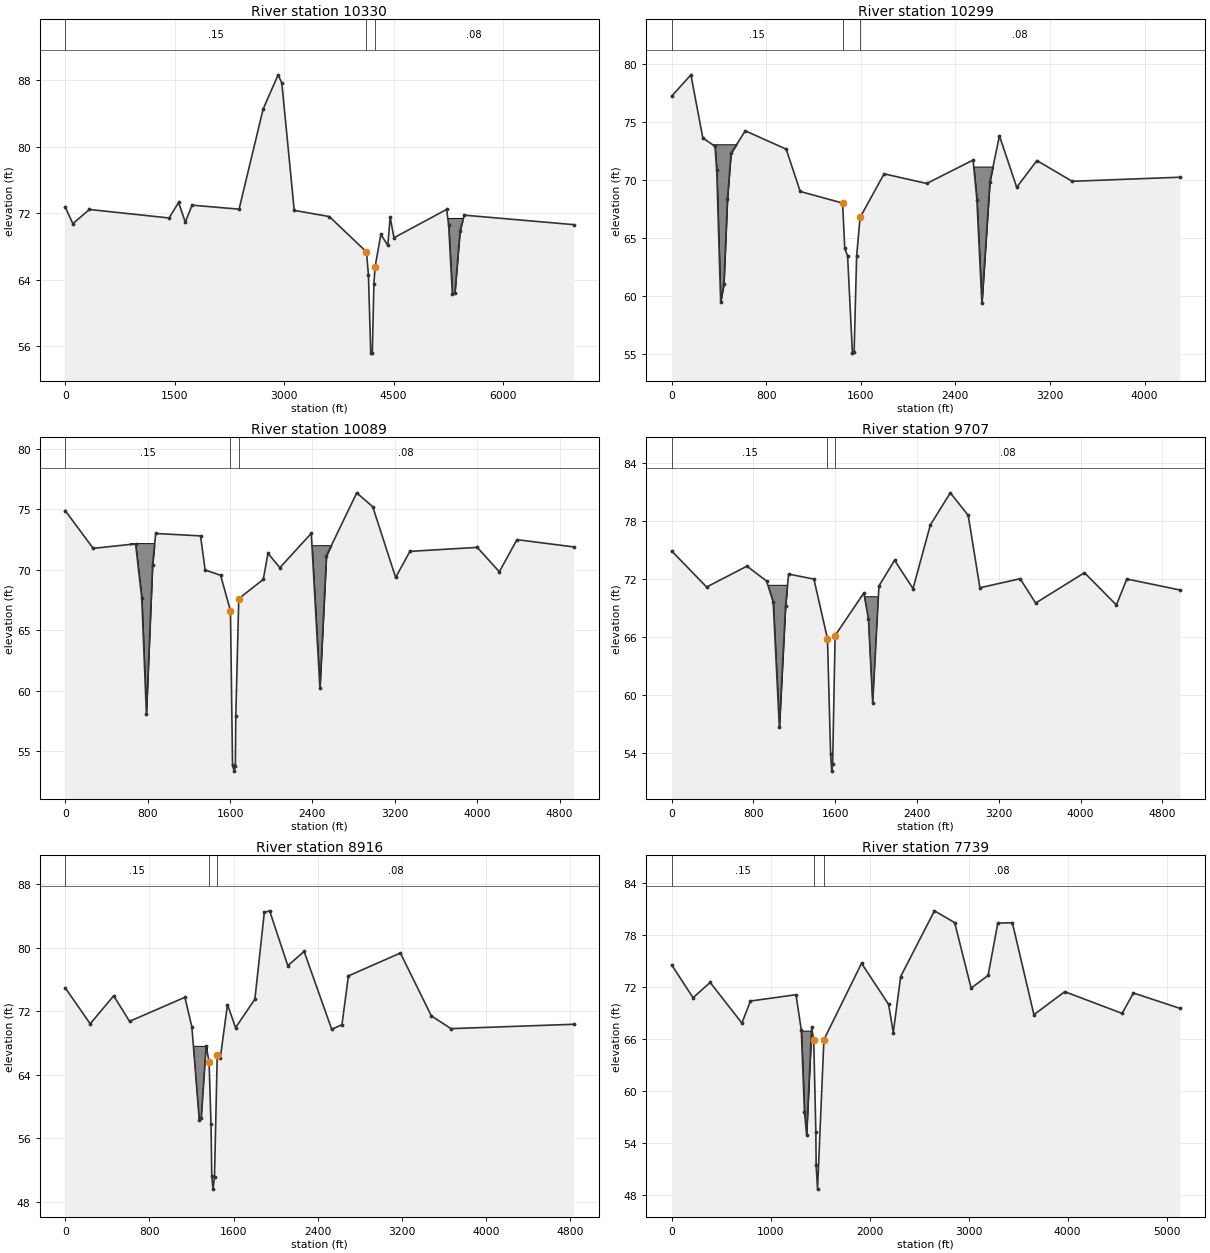
Type RM Length L Ch R = 1 ,10330   ,93.17,31.17,31.53
BEGIN DESCRIPTION:
S 10330.08
END DESCRIPTION:
XS GIS Cut Line= 6
     3063433.185    13806786.733     3062110.304    13804954.848
     3061798.769    13803979.717     3062258.534    13803268.168
     3062333.829    13803169.855     3064264.951    13801266.158
#Sta/Elev= 30
       0   72.74  104.54   70.74   332.1   72.44 1423.73   71.42 1553.25   73.29
 1645.76   70.91 1738.27   72.96  2382.8   72.48 2712.42   84.52 2918.19   88.63
 2968.51   87.64 3138.65   72.33  3619.3   71.59 4128.55   67.34 4155.16   64.58
 4187.26   55.18 4208.66   55.17 4230.06   63.48 4246.46   65.54 4325.73   69.44
 4420.93   68.12 4453.01   71.53 4505.18   69.04 5227.31   72.45 5254.75   70.54
 5305.58   62.31 5340.21   62.41 5410.89    69.9 5468.41   71.76 6965.98   70.62
#Mann= 3 , 0 , 0
       0     .15       0 4128.55     .04       0 4246.46     .08       0
#XS Ineff= 2 , 0
       0    3060            4600       0
Permanent Ineff=
       T       T
#Block Obstruct= 1 ,-1
 5239.42 5442.56   71.42
Bank Sta=4128.55,4246.46
XS Rating Curve= 0
Exp/Cntr=.5,.3

Type RM Length L Ch R = 1 ,10299   ,293.69,209.51,211.72
BEGIN DESCRIPTION:
Copied cross-section 10330
END DESCRIPTION:
XS GIS Cut Line= 5
     3062146.313     13804721.86     3062075.225    13804019.193
      3062281.03    13803289.835     3062356.325    13803191.521
     3064287.447    13801287.824
#Sta/Elev= 30
       0   77.26  162.76    79.1   263.4   73.66  366.22   72.93   381.3   70.86
  414.36   59.52   441.6   61.03  471.76   68.37  501.91   72.33  622.52   74.27
  968.79   72.69 1087.27   69.04 1445.74   68.04 1464.09   64.13 1488.11   63.48
  1528.7    55.1 1543.08   55.17 1564.47   63.48 1593.65    66.8 1796.67   70.56
  2157.3   69.73 2549.75   71.75 2581.57   68.34    2624   59.39 2691.88   69.89
  2772.5   73.84 2918.38    69.4 3089.31   71.71 3386.96   69.92 4299.62   70.27
#Mann= 3 , 0 , 0
       0     .15       0 1445.74     .04       0 1593.65     .08       0
#XS Ineff= 2 , 0
       0     940            1827       0
Permanent Ineff=
       T       T
#Block Obstruct= 2 ,-1
  296.77  580.65   73.11 2470.97 2793.55   71.19
Bank Sta=1445.74,1593.65
XS Rating Curve= 0
Exp/Cntr=.3,.1

Type RM Length L Ch R = 1 ,10089   ,346.88,381.98,385.64
BEGIN DESCRIPTION:
Surveyed cross-section
END DESCRIPTION:
XS GIS Cut Line= 4
     3062388.909    13804980.176     3062446.276    13803408.077
      3062526.45     13803317.92     3064839.607    13801048.032
#Sta/Elev= 30
       0   74.89  271.55   71.77  683.13   72.14  743.17   67.66   788.2    58.1
  848.24   70.42  878.26      73 1313.55    72.8 1358.58   69.98 1508.68   69.54
 1604.15   66.61 1624.47   53.82 1640.42   53.35 1651.83   53.74 1655.85   57.87
 1684.88   67.61 1922.84    69.2 1968.47   71.36 2083.76   70.17 2388.79   73.01
 2472.85    60.2  2535.9   71.16 2830.12   76.36 2985.36   75.21 3207.82   69.36
    3346   71.52 4000.22   71.85 4214.38   69.83 4385.28   72.49 4934.64   71.89
#Mann= 3 , 0 , 0
       0     .15       0 1604.15     .04       0 1684.88     .08       0
#XS Ineff= 2 , 0
       0    1085            1950       0
Permanent Ineff=
       T       T
#Block Obstruct= 2 ,-1
  625.81  864.52    72.2 2348.39 2664.52   72.03
Bank Sta=1604.15,1684.88
XS Rating Curve= 0
Exp/Cntr=.3,.1

Type RM Length L Ch R = 1 ,9707    ,721.48,791.46,741.38
BEGIN DESCRIPTION:
Surveyed cross-section
END DESCRIPTION:
XS GIS Cut Line= 4
     3062553.631    13805164.928     3062713.272    13803671.197
     3062790.473    13803593.289      3065272.84    13801328.165
#Sta/Elev= 30
       0   74.93   341.9    71.2   736.6   73.36  927.94   71.82  993.05   69.65
 1053.39   56.68 1113.73    69.2 1143.91   72.54 1391.32   72.02 1524.11   65.85
 1554.81   53.87    1566   52.14 1574.28   52.83 1598.77   66.18 1880.13   70.58
 1924.64   67.91 1966.63   59.16 2027.55   71.31 2180.19   73.97 2360.69   71.04
 2530.57   77.63 2725.77   80.95 2900.72   78.62 3015.07   71.12 3408.37   72.06
 3560.49   69.54 4037.87   72.68 4350.29   69.34 4452.38   72.03 4972.41   70.89
#Mann= 3 , 0 , 0
       0     .15       0 1524.11     .04       0 1598.77     .08       0
#XS Ineff= 2 , 0
       0    1350            1890       0
Permanent Ineff=
       T       T
#Block Obstruct= 2 ,-1
  890.32 1129.03   71.43 1851.61 2032.26   70.19
Bank Sta=1524.11,1598.77
XS Rating Curve= 0
Exp/Cntr=.3,.1

Type RM Length L Ch R = 1 ,8916    ,1066.29,1176.57,1142.21
BEGIN DESCRIPTION:
Surveyed cross-section
END DESCRIPTION:
XS GIS Cut Line= 5
     3062729.476    13805362.157      3063358.93    13804180.208
     3063405.152    13804054.432     3063714.951    13803539.462
     3065580.862    13801512.186
#Sta/Elev= 30
       0   74.98  237.53   70.44  460.33   73.97  611.41   70.75 1136.76   73.78
 1203.29   70.06  1274.2    58.3 1293.52   58.62 1339.11   67.63 1367.01   65.63
 1385.13   57.75 1392.32   51.31 1404.33    49.6  1418.4   51.14 1444.31    66.5
 1473.11   66.11 1541.81   72.87 1618.32   69.95 1802.13   73.55 1891.56   84.48
 1942.17   84.68 2114.76   77.77 2269.81   79.56 2532.05   69.74 2629.29   70.33
 2690.65   76.48 3184.41   79.36 3478.55   71.44 3665.23   69.83 4829.35   70.38
#Mann= 3 , 0 , 0
       0     .15       0 1367.01     .04       0 1444.31     .08       0
#XS Ineff= 2 , 0
       0    1135            1811       0
Permanent Ineff=
       T       T
#Block Obstruct= 1 ,-1
 1219.35 1348.39    67.6
Bank Sta=1367.01,1444.31
XS Rating Curve= 0
Exp/Cntr=.3,.1

Type RM Length L Ch R = 1 ,7739    ,1116.81,1165.8,1031.18
BEGIN DESCRIPTION:
Surveyed cross-section
END DESCRIPTION:
XS GIS Cut Line= 4
     3063326.736    13806032.043     3064183.345    13804906.472
     3064227.598    13804790.971     3066428.787    13801944.957
#Sta/Elev= 30
       0   74.57  215.92   70.77  388.99   72.54  709.44   67.84  795.87   70.39
 1256.08   71.12 1309.65   67.03 1341.76    57.6 1363.17   54.94 1414.46   67.35
 1435.41   65.83 1456.84   55.19 1459.63   51.39 1473.98   48.64 1538.15   65.92
 1918.36   74.75  2191.8      70 2239.15   66.74 2313.69   73.22 2655.03   80.82
 2859.33   79.46 3025.41   71.88 3197.04   73.35 3295.11   79.39 3442.22   79.45
 3660.06   68.81 3971.38   71.47 4551.32   68.96  4665.1   71.32 5136.07   69.54
#Mann= 3 , 0 , 0
       0     .15       0 1435.41     .04       0 1538.15     .08       0
#XS Ineff= 2 , 0
       0    1208            1905       0
Permanent Ineff=
       T       T
#Block Obstruct= 1 ,-1
 1246.45 1409.03   66.97
Bank Sta=1435.41,1538.15
XS Rating Curve= 0
Exp/Cntr=.3,.1

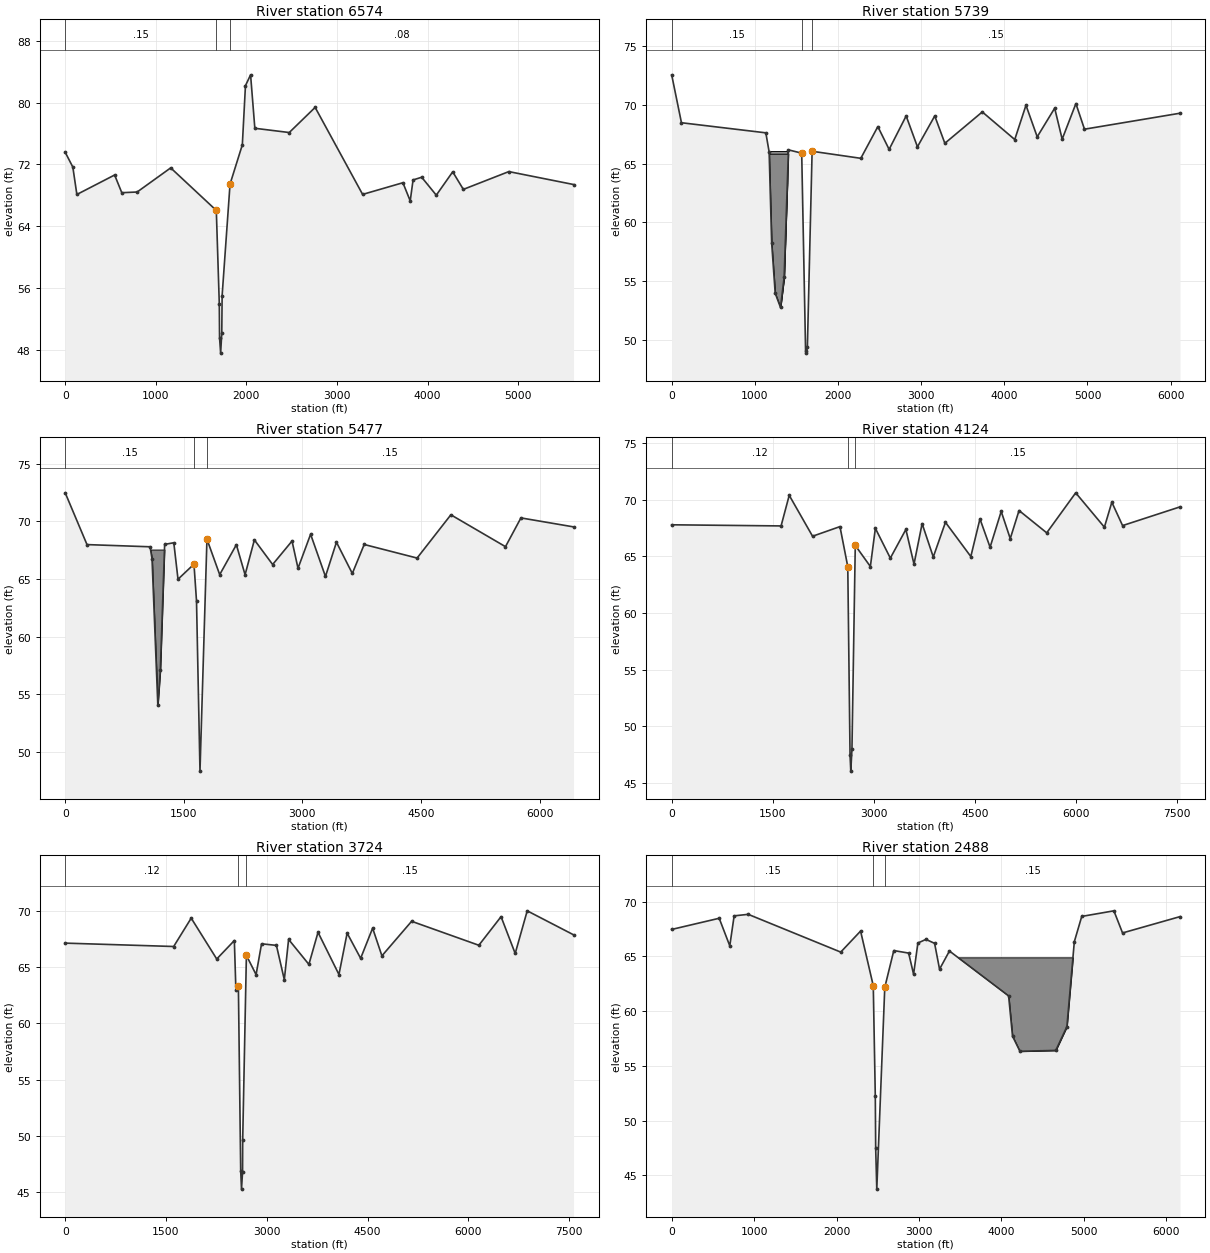
Type RM Length L Ch R = 1 ,6574    ,786.03,834.59,867.5
BEGIN DESCRIPTION:
Surveyed cross-section
END DESCRIPTION:
XS GIS Cut Line= 5
     3064217.323    13807030.924     3064403.285      13806933.9
     3064999.919    13805644.223     3065051.628    13805502.087
     3066495.355    13801956.046
#Sta/Elev= 30
       0   73.57    84.2   71.65  128.67   68.11  545.44   70.63  624.54   68.34
  794.04   68.43 1164.37   71.55 1667.79   66.05 1700.68   54.01 1703.55    49.6
  1715.7    47.6 1728.09   50.21 1732.07   55.05 1819.34   69.45    1955   74.53
 1989.52   82.18 2046.08   83.58 2093.11   76.67 2472.93   76.12 2758.69   79.37
 3282.66   68.12 3727.47   69.63 3808.04   67.28 3839.57   69.99 3934.65   70.34
 4095.78   68.02 4277.14   71.04 4394.44   68.77  4896.5   71.07 5610.68    69.4
#Mann= 3 , 0 , 0
       0     .15       0 1667.79     .04       0 1819.34     .08       0
#XS Ineff= 2 , 0
       0    1090            1970       0
Permanent Ineff=
       T       T
Bank Sta=1667.79,1819.34
XS Rating Curve= 0
Exp/Cntr=.3,.1

Type RM Length L Ch R = 1 ,5739    ,171.21,261.8,301.28
BEGIN DESCRIPTION:
Surveyed cross-section
END DESCRIPTION:
XS GIS Cut Line= 5
     3064399.759    13807235.544      3065562.55    13806233.191
     3065588.242    13806081.674     3066491.645    13804906.572
     3066586.327    13801966.284
#Sta/Elev= 30
       0   72.57  117.55   68.49 1132.44   67.63 1172.05      66 1202.39   58.27
 1244.93   53.97 1308.75   52.76 1352.45   55.32 1404.47   66.18 1563.67    65.9
 1610.34   49.08 1619.47   48.87 1631.86   49.35 1688.87   66.06 2274.36   65.46
 2479.31   68.16 2614.92   66.22 2819.74   69.07 2955.49   66.44 3163.62   69.07
 3285.22   66.74 3735.46   69.41 4125.66   67.06 4260.73   69.98  4395.8   67.29
 4605.91   69.73 4695.96   67.09 4861.04   70.12 4964.24   67.94 6112.91    69.3
#Mann= 3 , 0 , 0
       0     .15       0 1563.67     .04       0 1688.87     .15       0
#XS Ineff= 2 , 0
       0     937            1990       0
Permanent Ineff=
       T       T
#Block Obstruct= 2 ,-1
 1074.84 1390.97   66.08 1083.87 1418.06   65.85
Bank Sta=1563.67,1688.87
XS Rating Curve= 0
Exp/Cntr=.3,.1

Type RM Length L Ch R = 1 ,5477    ,1626.68,1353.14,1198.59
BEGIN DESCRIPTION:
Surveyed cross-section
END DESCRIPTION:
XS GIS Cut Line= 6
     3064677.701    13807547.284     3064694.865    13807218.538
     3065679.103      13806354.1     3065808.275    13806281.795
     3066855.976    13804910.762      3066990.66    13801997.853
#Sta/Elev= 30
       0   72.49  275.59   67.99  1073.3    67.8 1097.99   66.76 1171.48   54.02
 1203.36    57.1  1257.7   68.01 1373.42   68.15 1426.57   64.98 1628.52   66.29
  1660.5    63.1 1704.48    48.3 1792.58   68.46 1953.77   65.38  2164.7   67.98
  2274.8   65.37 2392.51    68.4 2623.23   66.26 2868.65    68.3 2944.16   65.93
 3103.47   68.89 3291.39   65.22  3430.5    68.2 3631.08   65.48 3781.25      68
 4450.18   66.82 4877.42   70.58 5568.15   67.81 5763.36   70.31 6428.72   69.53
#Mann= 3 , 0 , 0
       0     .15       0 1628.52     .04       0 1792.58     .15       0
#XS Ineff= 2 , 0
       0    1077            1990       0
Permanent Ineff=
       T       T
#Block Obstruct= 1 ,-1
 1047.74 1309.68   67.56
Bank Sta=1628.52,1792.58
XS Rating Curve= 0
Exp/Cntr=.3,.1

Type RM Length L Ch R = 1 ,4124    ,352.28,399.88,404.12
BEGIN DESCRIPTION:
Surveyed cross-section
END DESCRIPTION:
XS GIS Cut Line= 5
     3066680.389    13809530.354     3066898.325    13806967.202
     3066898.325    13806815.628     3067058.878     13804928.74
     3067163.345     13802006.57
#Sta/Elev= 30
       0   67.77 1623.28   67.67 1744.12   70.37 2090.37   66.76 2496.83   67.61
 2612.72   64.08 2646.38   47.43 2657.44   46.04 2674.79      48 2723.97   65.95
 2947.91   64.09 3022.08   67.46 3244.05   64.83  3474.8   67.36 3595.24    64.3
 3715.67   67.87 3881.27   64.93 4061.92   67.99 4438.28   64.97 4573.76   68.29
 4723.99   65.79 4889.09   68.95 5023.31   66.55 5153.73   69.03 5564.52   67.06
 5994.24   70.59 6420.07   67.56 6530.43   69.76 6689.83    67.7 7541.72   69.35
#Mann= 3 , 0 , 0
       0     .12       0 2612.72     .04       0 2723.97     .15       0
#XS Ineff= 2 , 0
       0    2111            2990       0
Permanent Ineff=
       T       T
Bank Sta=2612.72,2723.97
XS Rating Curve= 0
Exp/Cntr=.3,.1

Type RM Length L Ch R = 1 ,3724    ,1196.56,1235.82,1221.92
BEGIN DESCRIPTION:
Surveyed cross-section
END DESCRIPTION:
XS GIS Cut Line= 5
     3066833.121    13809523.412     3067237.304    13807015.865
     3067296.675    13806871.371     3067516.382    13804950.939
     3067682.917    13802020.817
#Sta/Elev= 30
       0   67.14 1614.02   66.84  1874.8   69.36 2254.64   65.73 2516.85   67.37
 2539.91   62.97 2576.86   63.35 2611.26   46.93 2623.36   45.28 2639.12   46.83
 2640.98   49.62 2696.13   66.05 2840.36   64.34 2921.65   67.08  3142.9   66.94
 3260.35   63.89 3324.07   67.47 3626.03   65.25 3761.91    68.1 4073.22   64.35
 4195.16   68.03 4396.02   65.79  4574.5   68.47 4712.66   66.01 5154.67   69.08
 6154.99   66.95 6485.52   69.49 6695.86   66.22 6874.83   70.01 7563.94   67.88
#Mann= 3 , 0 , 0
       0     .12       0 2576.86     .04       0 2696.13     .15       0
#XS Ineff= 2 , 0
       0    1978            2920       0
Permanent Ineff=
       T       T
Bank Sta=2576.86,2696.13
XS Rating Curve= 0
Exp/Cntr=.3,.1

Type RM Length L Ch R = 1 ,2488    ,648.44,663.49,590.71
BEGIN DESCRIPTION:
Surveyed cross-section
END DESCRIPTION:
XS GIS Cut Line= 4
     3066859.505    13809772.222     3068131.044     13807713.93
     3068216.844    13807571.885     3068247.269     13803990.57
#Sta/Elev= 30
       0   67.47  576.51   68.49  704.93   65.97  757.82   68.71  928.36   68.85
 2050.92    65.4 2291.76   67.32  2445.7   62.33 2470.21   52.25 2474.99   47.47
 2488.32   43.75 2585.32   62.18 2694.71   65.54 2874.72   65.31 2934.72   63.38
 2986.97   66.23 3084.73   66.56 3189.73    66.2 3249.73   63.84 3369.74    65.5
 4087.65    61.4 4134.76   57.73 4224.77   56.34 4659.78   56.42 4794.79   58.59
 4884.79   66.35 4974.79   68.66 5364.81   69.17 5469.81   67.15 6166.77   68.64
#Mann= 3 , 0 , 0
       0     .15       0  2445.7     .04       0 2585.32     .15       0
#XS Ineff= 2 , 0
       0    2343            2986       0
Permanent Ineff=
       T       T
#Block Obstruct= 1 ,-1
 3468.39 4868.39   64.92
Bank Sta=2445.7,2585.32
XS Rating Curve= 0
Exp/Cntr=.3,.1

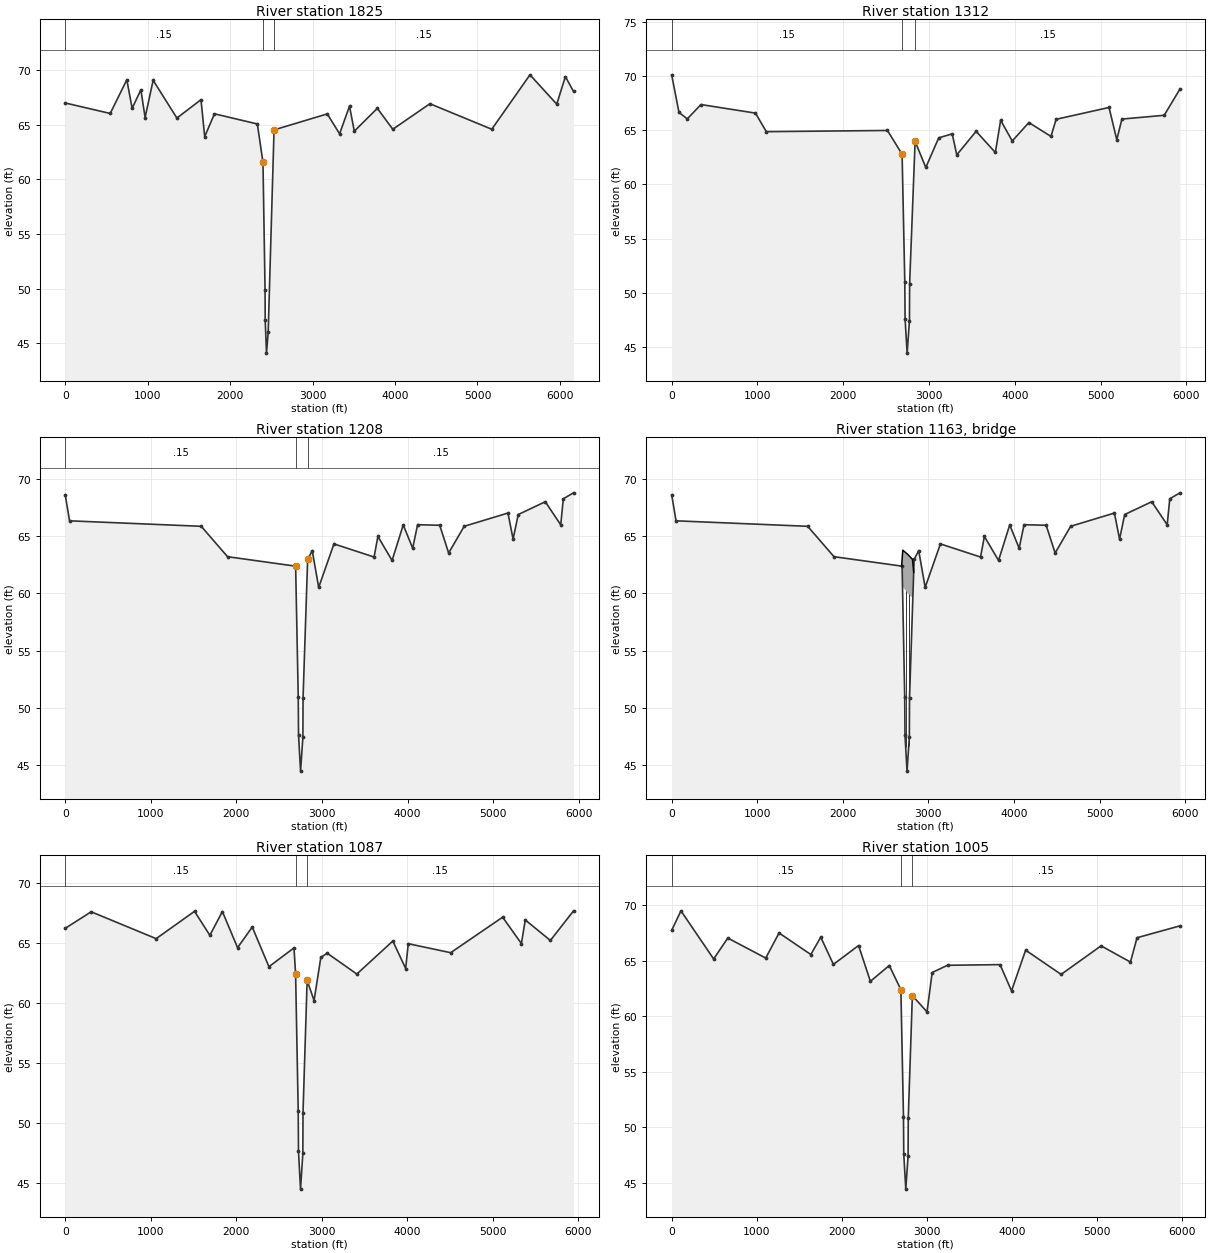
Type RM Length L Ch R = 1 ,1825    ,539.26,512.88,523.9
BEGIN DESCRIPTION:
Surveyed cross-section
END DESCRIPTION:
XS GIS Cut Line= 5
     3066992.796     13809953.84     3068585.294    13808178.564
     3068673.708    13808072.513     3068742.021    13804823.592
     3068590.353      13804461.3
#Sta/Elev= 30
       0   66.97  545.87   66.01  747.38   69.09  811.57   66.48  917.79   68.17
  969.04   65.64  1066.5   69.04 1354.86   65.59 1646.89   67.27 1691.81   63.89
 1810.06   65.98 2330.54   65.05 2398.67   61.54 2423.98   49.86 2425.85   47.11
 2441.38   44.12 2461.87   46.02 2532.97   64.51 3178.11   65.97 3328.14   64.15
 3448.17   66.68  3506.3   64.39 3785.49   66.48 3973.28   64.57 4423.38    66.9
 5173.55   64.57 5636.98   69.54 5961.99   66.86 6066.48   69.38 6165.35   68.02
#Mann= 3 , 0 , 0
       0     .15       0 2398.67     .04       0 2532.97     .15       0
#XS Ineff= 2 , 0
       0    2231            2889       0
Permanent Ineff=
       T       T
Bank Sta=2398.67,2532.97
XS Rating Curve= 0
Exp/Cntr=.3,.1

Type RM Length L Ch R = 1 ,1312    ,104.43,104.43,106.06
BEGIN DESCRIPTION:
Copied cross-section 1087/XS1
END DESCRIPTION:
XS GIS Cut Line= 4
      3067206.44     13810359.05     3069058.149     13808428.05
     3069115.785    13808291.878     3069356.181    13805184.217
#Sta/Elev= 30
       0   70.11   85.28   66.64   182.2   66.05  341.33   67.37  976.78   66.58
 1103.61   64.87  2515.5   64.98 2686.74   62.79 2718.16   50.98 2721.54   47.61
 2745.31   44.45 2772.49   47.43  2774.3   50.82 2838.22   63.97 2963.03   61.57
 3113.48    64.3 3271.12   64.67  3324.1   62.73 3549.78    64.9 3773.84   62.95
 3835.63   65.92 3971.03   64.01 4164.85   65.71 4422.38   64.43 4482.55   66.01
 5099.39    67.1 5189.66   64.13 5249.84   66.03 5742.85   66.38 5926.86   68.81
#Mann= 3 , 0 , 0
       0     .15       0 2686.74     .04       0 2838.22     .15       0
#XS Ineff= 2 , 0
       0    2667            2866       0
Permanent Ineff=
       T       T
Bank Sta=2686.74,2838.22
XS Rating Curve= 0
Exp/Cntr=.5,.3

Type RM Length L Ch R = 1 ,1208    ,120.7,120.86,117.47
BEGIN DESCRIPTION:
Copied cross-section 1087/XS2
END DESCRIPTION:
XS GIS Cut Line= 4
      3067301.08     13810403.19     3069152.786     13808472.19
     3069210.422    13808336.018     3069450.818    13805228.357
#Sta/Elev= 30
       0   68.64      51   66.36  1589.3   65.88 1896.95   63.22 2692.72   62.39
 2723.16   50.98 2726.54   47.61 2750.31   44.45 2777.49   47.43  2779.3   50.82
  2833.1   62.98 2886.94   63.75 2962.16   60.53 3140.32   64.34 3609.09   63.19
 3654.23   64.99 3819.72   62.89 3950.26      66 4060.44   63.96 4117.84   66.02
 4376.38   65.97 4480.92   63.54 4662.23   65.88 5173.75   67.04 5233.93   64.76
 5294.11   66.91 5610.05   68.03 5790.59   66.01 5820.68   68.29 5940.18   68.81
#Mann= 3 , 0 , 0
       0     .15       0 2692.72     .04       0  2833.1     .15       0
#XS Ineff= 2 , 0
       0    2668            2869       0
Permanent Ineff=
       T       T
Bank Sta=2692.72,2833.1
XS Rating Curve= 0
Exp/Cntr=.5,.3

Type RM Length L Ch R = 3 ,1163    ,,,
BEGIN DESCRIPTION:
Braeswood Bridge
END DESCRIPTION:
Bridge Culvert--1,0,-1,-1, 0
Deck Dist Width WeirC Skew NumUp NumDn MinLoCord MaxHiCord MaxSubmerge Is_Ogee
16.43,88,2.6,0, 7, 7, , , .95, 0, 0,0,,
    2687    2701    2701    2757    2814    2814 2828.62
   62.39   63.79   63.79   63.43   62.99   62.99   61.85
       0       0   60.58   60.04   59.59       0       0
    2689    2703    2703    2760    2816    2816 2830.62
   62.39   63.79   63.79   63.43   62.99   62.99   61.85
     -.3       0   60.58   60.04   59.59       0     -.3
Pier Skew, UpSta & Num, DnSta & Num=  ,2734.39, 2 ,2731.39, 2 , 0 , 0 , 0 ,,
     1.4     1.4
     -.1      61
     1.4     1.4
     -.1      61
Pier Skew, UpSta & Num, DnSta & Num=  ,2770.39, 2 ,2773.39, 2 , 0 , 0 , 0 ,,
     1.4     1.4
       0      61
     1.4     1.4
       0      61
BR Coef=-1 , 1 , 1 ,1.25, 0 ,,,.8,-1,2,0,
WSPro=,,,, 1 ,,,, 0 ,,,, 0 ,,,,-1 ,-1 ,-1 , 0 , 0 , 0 , 0 , 0
BC Design=,, 0 ,, 0 ,,,,,,

Type RM Length L Ch R = 1 ,1087    ,82.08,81.91,81.12
BEGIN DESCRIPTION:
Surveyed cross-section/XS3
END DESCRIPTION:
XS GIS Cut Line= 4
      3067390.23     13810444.78     3069262.344    13808523.225
      3069319.98    13808387.053     3069560.376    13805279.392
#Sta/Elev= 30
       0   66.19  303.76   67.57 1064.25   65.33 1513.02   67.61 1692.51   65.61
  1839.1   67.59 2016.63   64.58 2188.59    66.3  2383.6   62.99 2676.78   64.56
 2695.72   62.39 2726.16   50.98 2729.54   47.61 2753.31   44.45 2780.49   47.43
  2782.3   50.82 2830.62   61.86 2911.68   60.17 2990.65   63.76 3065.29   64.12
  3411.9   62.38 3833.16   65.13 3983.61   62.84  4013.7   64.91 4510.17   64.16
 5118.08   67.12 5337.64   64.92 5382.78   66.89 5676.67   65.18 5947.56   67.65
#Mann= 3 , 0 , 0
       0     .15       0 2695.72     .04       0 2830.62     .15       0
#XS Ineff= 2 , 0
       0    2676            2970       0
Permanent Ineff=
       T       T
Bank Sta=2695.72,2830.62
XS Rating Curve= 0
Exp/Cntr=.5,.3

Type RM Length L Ch R = 1 ,1005    ,383.19,384.84,361.32
BEGIN DESCRIPTION:
Copied cross-section 1087/XS4
END DESCRIPTION:
XS GIS Cut Line= 4
      3067484.84     13810488.91      3069336.55     13808557.91
     3069394.186    13808421.738     3069677.246    13805279.392
#Sta/Elev= 30
       0   67.73  108.97   69.49   493.8   65.16  660.06   67.04 1106.21   65.24
 1262.74    67.5 1636.48   65.56 1753.35   67.12 1901.88   64.67 2197.95   66.37
 2336.84   63.15 2559.63   64.57 2695.72   62.39 2726.16   50.98 2729.54   47.61
 2753.31   44.45 2780.49   47.43  2782.3   50.82 2830.62   61.86  3003.2    60.4
 3063.44   63.94 3244.17   64.59 3861.66   64.65 3997.21   62.29 4162.88   65.95
 4580.24   63.77 5049.99   66.34  5395.4   64.88 5473.16   67.07 5978.31   68.14
#Mann= 3 , 0 , 0
       0     .15       0 2695.72     .04       0 2830.62     .15       0
#XS Ineff= 2 , 0
       0    2669            3020       0
Permanent Ineff=
       T       T
Bank Sta=2695.72,2830.62
XS Rating Curve= 0
Exp/Cntr=.3,.1

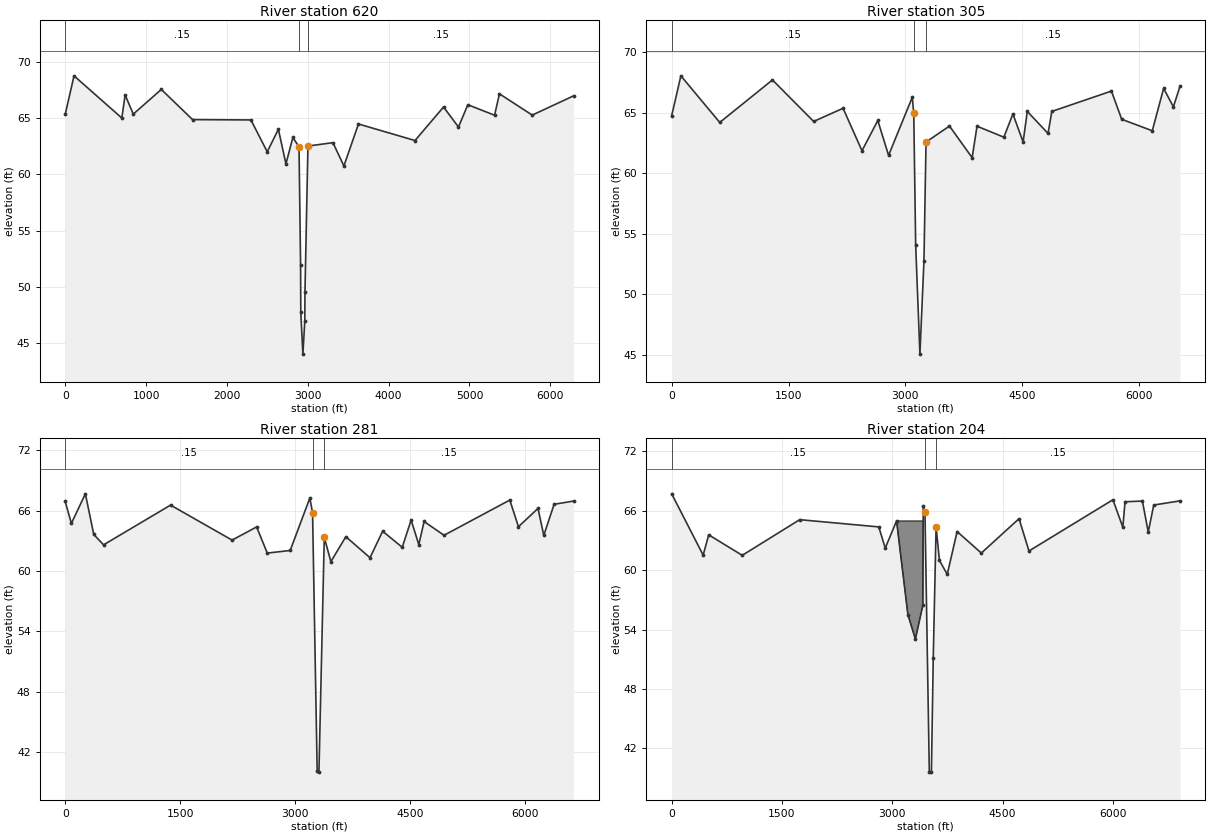
Type RM Length L Ch R = 1 ,620     ,339.42,314.56,297.78
BEGIN DESCRIPTION:
Surveyed cross-section
END DESCRIPTION:
XS GIS Cut Line= 4
     3067575.957    13810641.136     3069696.729    13808699.162
     3069742.915    13808581.182     3069946.048    13805302.766
#Sta/Elev= 30
       0   65.33  109.04   68.76  700.39   65.01  741.06   67.06  842.01   65.36
 1188.51   67.55 1574.95   64.87 2296.91   64.84 2498.63   62.01 2636.65   64.01
 2729.96   60.93  2815.6   63.28  2891.8   62.45 2911.13   51.95 2913.58   47.74
 2939.64   44.03 2963.15   46.96 2965.48   49.57 3002.27   62.52 3311.55   62.82
 3446.81   60.75 3627.15   64.48  4326.2   63.01 4679.17   65.99 4863.97   64.21
 4979.74   66.19 5310.37   65.26 5370.49   67.16 5776.26   65.27 6286.98   66.98
#Mann= 3 , 0 , 0
       0     .15       0  2891.8     .04       0 3002.27     .15       0
#XS Ineff= 2 , 0
       0    2871            3066       0
Permanent Ineff=
       T       T
Bank Sta=2891.8,3002.27
XS Rating Curve= 0
Exp/Cntr=.3,.1

Type RM Length L Ch R = 1 ,305     ,26.67,23.94,27.57
BEGIN DESCRIPTION:
Surveyed cross-section
END DESCRIPTION:
XS GIS Cut Line= 4
     3067721.747    13810828.581     3070027.753    13808772.748
     3070042.039    13808584.255     3070144.727    13805337.827
#Sta/Elev= 30
       0   64.74  118.16   68.03  617.27   64.18 1293.97   67.69    1823   64.26
 2200.47   65.35 2443.55   61.84 2646.42   64.34  2784.8   61.46 3089.36   66.26
 3108.11   64.93 3132.75   54.05 3187.13   45.04 3238.89    52.7  3265.8   62.56
 3566.64   63.88 3857.58   61.27 3920.46   63.87 4264.91   62.96 4381.29   64.88
 4512.21   62.56 4565.79   65.09 4832.26   63.27 4880.95   65.09 5646.33   66.77
 5777.83   64.44 6170.61   63.49 6316.09   66.99 6441.73   65.47 6526.44   67.17
#Mann= 3 , 0 , 0
       0     .15       0 3108.11     .04       0  3265.8     .15       0
#XS Ineff= 2 , 0
       0    3072            3307       0
Permanent Ineff=
       T       T
Bank Sta=3108.11,3265.8
XS Rating Curve= 0
Exp/Cntr=.3,.1

Type RM Length L Ch R = 1 ,281     ,85.01,77.22,69.82
BEGIN DESCRIPTION:
Surveyed cross-section
END DESCRIPTION:
XS GIS Cut Line= 5
     3067756.459    13810960.486     3069033.859     13810071.86
     3070051.808    13808773.722     3070065.944    13808584.381
     3070226.536    13805349.514
#Sta/Elev= 30
       0    66.9   80.45   64.72  263.17   67.66  372.81   63.62  500.72   62.59
 1375.05   66.54 2177.89   63.06 2498.41   64.37  2637.3   61.77 2936.45   62.03
 3192.86   67.24 3228.43   65.77 3288.61   40.07 3311.64      40 3381.28   63.33
 3467.58   60.92 3662.82    63.4 3978.21   61.31 4142.92   63.94 4398.73   62.35
 4514.93   65.05 4615.09   62.61 4684.08   64.91 4944.17   63.54 5802.66   67.04
 5915.59   64.39 6170.91   66.21    6246   63.53 6381.17   66.62 6634.46   66.94
#Mann= 3 , 0 , 0
       0     .15       0 3228.43     .04       0 3381.28     .15       0
#XS Ineff= 2 , 0
       0    3184            3424       0
Permanent Ineff=
       T       T
Bank Sta=3228.43,3381.28
XS Rating Curve= 0
Exp/Cntr=.3,.1

Type RM Length L Ch R = 1 ,204     ,11.43,204.23,28.71
BEGIN DESCRIPTION:
Surveyed cross-section
END DESCRIPTION:
XS GIS Cut Line= 5
     3067784.229    13811064.622     3069353.209     13810217.65
     3070136.801    13808778.813     3070136.801    13808558.538
     3070296.658    13805291.079
#Sta/Elev= 30
       0    67.7  428.33   61.51  503.73   63.56   959.7   61.49 1741.21   65.09
 2816.48   64.36 2904.76   62.22 3058.48   64.97 3212.21   55.51 3314.69   53.03
 3415.48   56.44 3421.37   66.49 3444.66   65.83 3503.75   39.65 3532.36    39.6
 3557.39   51.15 3595.94   64.34 3641.64   60.97 3747.81   59.57 3881.92   63.89
 4211.23   61.72 4723.97   65.19 4859.13   61.93  6000.5    67.1 6135.66   64.33
  6165.7    66.9  6401.8   66.97 6481.07   63.84 6556.16   66.57 6913.01   66.99
#Mann= 3 , 0 , 0
       0     .15       0 3444.66     .04       0 3595.94     .15       0
#XS Ineff= 2 , 0
       0    3382            3646       0
Permanent Ineff=
       T       T
#Block Obstruct= 1 ,-1
 3057.59 3423.64   64.96
Bank Sta=3444.66,3595.94
XS Rating Curve= 0
Exp/Cntr=.3,.1

Chan Stop Cuts=-1